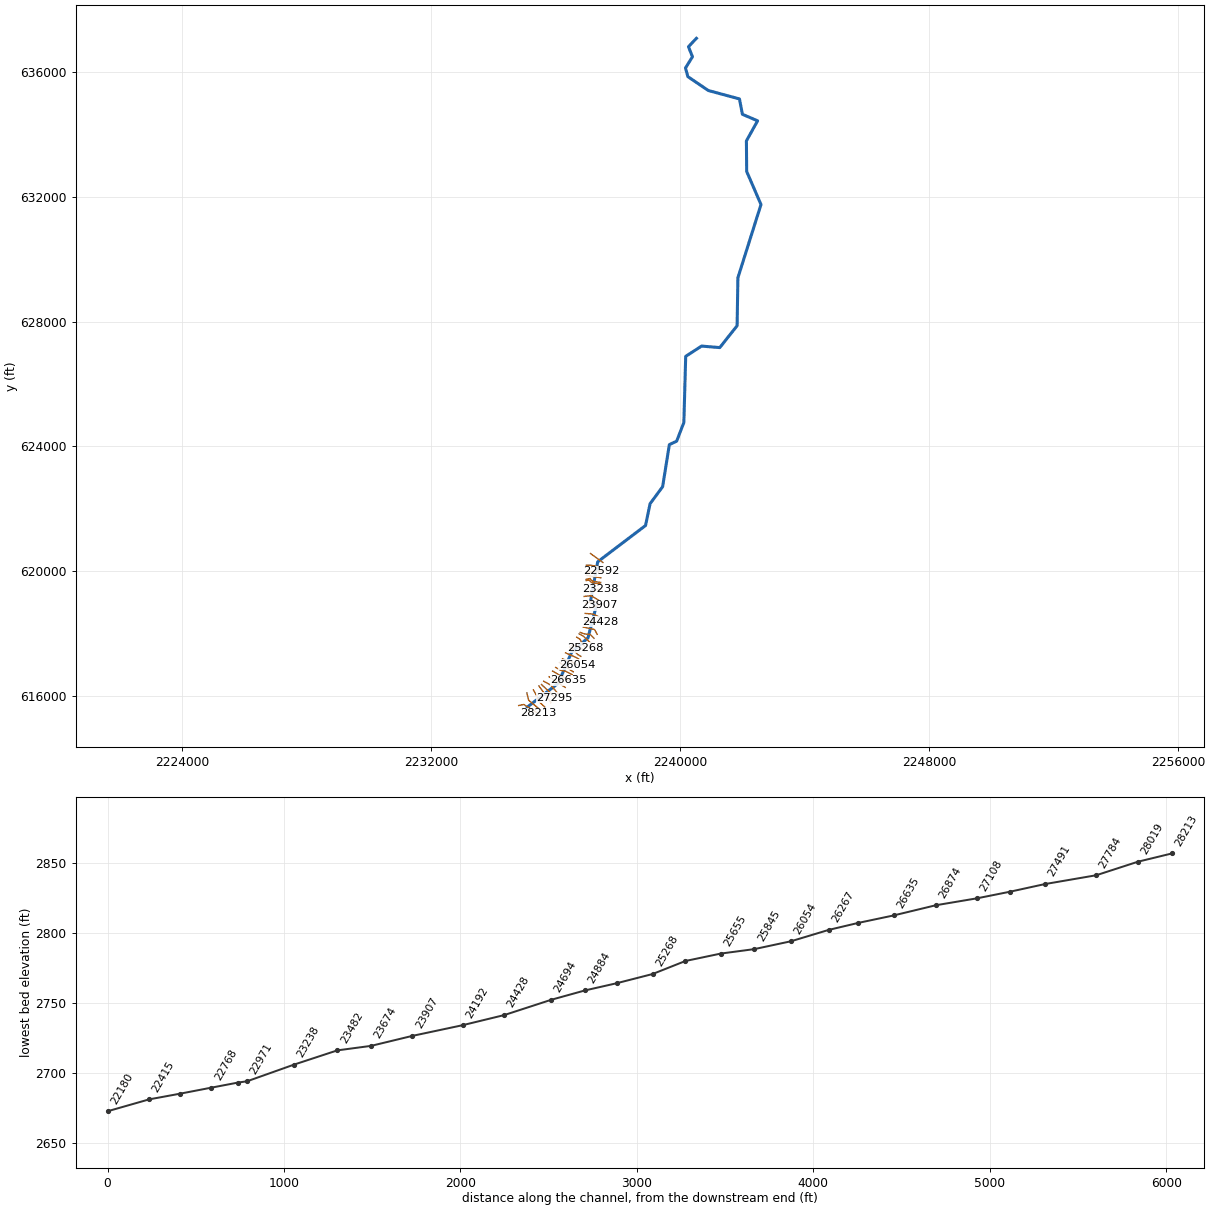
--- KITTLECK.prj (project) ---

Proj Title=KITTLECK
Current Plan=p01
Default Exp/Contr=0,0
English Units
Geom File=g01
Flow File=f01
Plan File=p01
BEGIN DESCRIPTION:
----------MODEL BY WSP USA 2022----------
AFH study
Randolph County, WV
HEC-RAS Version: RAS 6.2
Vertical Datum: NAVD88
Projection: NAD 1983 StatePlane West Virginia S FIPS 4702 (US Feet)
Terrain: 1-meter LIDAR (FEMA Region III 3DEP collected 2016-2018)
Land Use: 2019 NLCD
Hydrologic Method:
WV SIR2010-5033 regression equations
Additional Model Notes:
KWSE with MIDFKRIV and BIRCHFK due to coincident peak
END DESCRIPTION:
DSS Export Rating Curves= 0
DSS Export Rating Curve Sorted= 0
DSS Export Volume Flow Curves= 0
DXF OffsetX= 0
DXF OffsetY= 0
DXF ScaleX= 0
DXF ScaleY= 0

--- KITTLECK.p01 (plan) ---

Plan Title=Floodplain
Program Version=6.20
Short Identifier=Floodplain
Geom File=g01
Flow File=f01
Subcritical Flow
K Sum by GR= 0
Std Step Tol= 0.01
Critical Tol= 0.01
Num of Std Step Trials= 20
Max Error Tol= 0.3
Flow Tol Ratio= 0.001
Split Flow NTrial= 30
Split Flow Tol= 0.02
Split Flow Ratio= 0.02
Log Output Level= 0
Friction Slope Method= 1
Unsteady Friction Slope Method= 2
Unsteady Bridges Friction Slope Method= 1
Parabolic Critical Depth
Global Vel Dist= 0 , 0 , 0
Global Log Level= 0
CheckData=True
Encroach Param=-1 ,0,0, 0
Mapping Interval=1HOUR
Computation Time Step Use Courant=        0
Computation Time Step Use Time Series=    0
Computation Time Step Count To Double=0
Computation Time Step Max Doubling=0
Computation Time Step Max Halving=0
Computation Time Step Residence Courant=0
Run HTab= 0
Run UNet= 0
Run Sediment= 0
Run PostProcess= 0
Run WQNet= 0
Run RASMapper=-1
UNET Theta= 0
UNET Theta Warmup= 0
UNET ZTol= 0
UNET ZSATol= 0
UNET MxIter= 0
UNET Max Iter WO Improvement= 0
UNET MaxInSteps= 0
UNET DtIC= 0
UNET DtMin= 0
UNET MaxCRTS= 0
UNET WFStab= 0
UNET SFStab= 0
UNET WFX= 1
UNET SFX= 1
UNET Gravity=32.174
UNET 1D Methodology=Finite Difference
UNET DSS MLevel= 1
UNET Pardiso=0
UNET DZMax Abort= 0
UNET Use Existing IB Tables= 0
UNET Froude Reduction=False
UNET Froude Limit= 0
UNET Froude Power= 0
UNET D1 Cores= 0
UNET WindReference=Eulerian
UNET WindDragFormulation=Hsu (1988)
UNET D2 Coriolis=0
UNET D2 Cores= 0
UNET D2 Theta= 1
UNET D2 Theta Warmup= 1
UNET D2 Z Tol= 0.01
UNET D2 Volume Tol= 0.01
UNET D2 Max Iterations= 20
UNET D2 Equation= 0
UNET D2 RampUpFraction=0.1
UNET D2 TimeSlices= 1
UNET D2 Turbulence Formulation=Non-Conservative (original)
UNET D2 Eddy Viscosity=0.3
UNET D2 Transverse Eddy Viscosity=0.1
UNET D2 Smagorinsky Mixing=0
UNET D2 BCVolumeCheck=0
UNET D2 Cores=0
UNET D2 SolverType=PARDISO (Direct)
UNET D2 Minimum Iterations= 2147483647
UNET D2 Maximum Iterations= 2147483647
UNET D2 Restart Number= 10
UNET D2 Relaxation Coeff=1.3
UNET D2 SOR Precondition Iterations= 10
UNET D2 ILUT Maximum Fill= 8
UNET D2 ILUT Tolerance=1E-08
UNET D1D2 MaxIter= 0
UNET D1D2 ZTol=0.01
UNET D1D2 QTol=0.1
UNET D1D2 MinQTol=1
Write IC File= 0
Write IC File at Fixed DateTime=0
Write IC File at Sim End=0
Echo Input=False
Echo Parameters=False
Echo Output=False
Write Detailed= 0
HDF Write Warmup=0
HDF Write Time Slices=0
HDF Flush=0
HDF Compression= 1
HDF Chunk Size= 1
HDF Spatial Parts= 1
HDF Use Max Rows=0
HDF Fixed Rows= 1
Calibration Method= 0
Calibration Iterations= 20
Calibration Max Change=0.05
Calibration Tolerance=0.2
Calibration Maximum=1.5
Calibration Minimum=0.5
Calibration Optimization Method= 1
WQ AD Non Conservative
WQ ULTIMATE=-1
WQ Max Comp Step=1HOUR
WQ Output Interval=15MIN
WQ Output Selected Increments= 0
WQ Output face flow=0
WQ Output face velocity=0
WQ Output face area=0
WQ Output face dispersion=0
WQ Output cell volume=0
WQ Output cell surface area=0
WQ Output cell continuity=0
WQ Output cumulative cell continuity=0
WQ Output face conc=0
WQ Output face dconc_dx=0
WQ Output face courant=0
WQ Output face peclet=0
WQ Output face adv mass=0
WQ Output face disp mass=0
WQ Output cell mass=0
WQ Output cell source sink temp=0
WQ Output nsm pathways=0
WQ Output nsm derived pathways=0
WQ Create Restart=0
WQ Fixed Restart=0
WQ System Summary=0
WQ Write To DSS=0
Sorting and Armoring Iterations= 10
XS Update Threshold= 0.02
Bed Roughness Predictor= 0
Hydraulics Update Threshold= 0.02
Energy Slope Method= 1
Volume Change Method= 1
Sediment Retention Method= 0
Sediment TS Multiplier= 1
Warm Up Method= 0
XS Weighting Method= 0
Number of US Weighted Cross Sections= 1
Number of DS Weighted Cross Sections= 1
Upstream XS Weight=0
Main XS Weight=1
Downstream XS Weight=0
Number of DS XS's Weighted with US Boundary= 1
Upstream Boundary Weight= 1
Weight of XSs Associated with US Boundary= 0
Number of US XS's Weighted with DS Boundary= 1
Downstream Boundary Weight= 0.5
Weight of XSs Associated with DS Boundary= 0.5
Percentile Method= 0
Sediment Output Level= 3
Mass or Volume Output= 0
Output Increment Type= 1
Profile and TS Output Increment= 1
Transport Output Increment 1
XS Output Flag= 0
XS Output Increment= 10
Read HDF5 Sediment Hotstart= 0
Sediment Hotstart Type= 0
Write Gradation File= 0
Read Gradation Hotstart= 0
Write HDF5 File= 1
Write Binary Output= 1
Write DSS Sediment File= 0
DSS Sediment Output Type= 1
SV Curve= 0
Specific Gage Flag= 0
Subcell Erosion Methods= 0
Subcell Deposition Methods= 0
Advection Scheme= 1
Matrix Solver= 0
Implicit Weighting Factor= 1
Maximum Outer Loop Convergence Iterations= 5
Convergence Maximum Absolute= 0.001
Convergence RMSE= 0.0001
Grain Fractions Max Abs Error= 0.001
Max Subgrid Regions= 1
Max Subgrid Length Scale= 3.402823E+38
Initial Layer Thickness= 3.402823E+38
Min Layer Thickness= 3.402823E+38
Max Layer Thickness= 3.402823E+38
Number of Layers= 5

--- KITTLECK.f01 (steady flow) ---

Flow Title=Flow
Program Version=6.20
Number of Profiles= 1
Profile Names=P100yr
River Rch & RM=KITTLECK,Main            ,28213
     432
River Rch & RM=KITTLECK,Main            ,24428
     551
River Rch & RM=KITTLECK,Main            ,21386
     702
River Rch & RM=KITTLECK,Main            ,20624
     805
River Rch & RM=KITTLECK,Main            ,17558
     933
River Rch & RM=KITTLECK,Main            ,13795
    1040
River Rch & RM=KITTLECK,Main            ,11412
    1180
River Rch & RM=KITTLECK,Main            ,8570
    1330
River Rch & RM=KITTLECK,Main            ,2964
    1600
River Rch & RM=KITTLECK,Main            ,0
    4040
Boundary for River Rch & Prof#=KITTLECK,Main            , 1
Up Type= 0
Dn Type= 1
Dn Known WS=2309.7
DSS Import GetInterval= 0
DSS Import GetPeak= 0
DSS Import FillOption= 0

--- KITTLECK.g01 (geometry) ---

Geom Title=Geometry
Program Version=6.20

River Reach=KITTLECK        ,Main
Reach XY= 30
 2235094.6680879615629.8533681332236087.44644868616395.051725224
2236520.35600004617396.5310000032237043.27199999617851.392000005
2237306.51270145 618857.608266222237125.40099999619030.145000011
2237355.99699999620293.4080000072238892.06567112621457.791194335
2239037.91955739622157.9439799042239440.42938469622702.387652293
2239656.91400005624054.381000012 2239892.1662367624165.453373224
2240122.65700004      624763.8162240181.68648806 626887.53602536
2240691.62199999627216.7630000112241275.76300003627168.244000018
2241833.04200001627869.5890000022241858.04100002629408.825000003
2242599.86754589631759.909149125     2242140.333632820.630999997
2242131.40099999633802.3320000022242490.60100003 634447.07600002
2242002.43000002634656.6260000022241908.71418937635149.179056168
2240907.00000003635419.9360000192240251.94600001635863.639000013
2240175.40300003      636142.8532240399.01400001636502.228000015
     2240270.542636825.1450000112240525.49747127637094.041837811

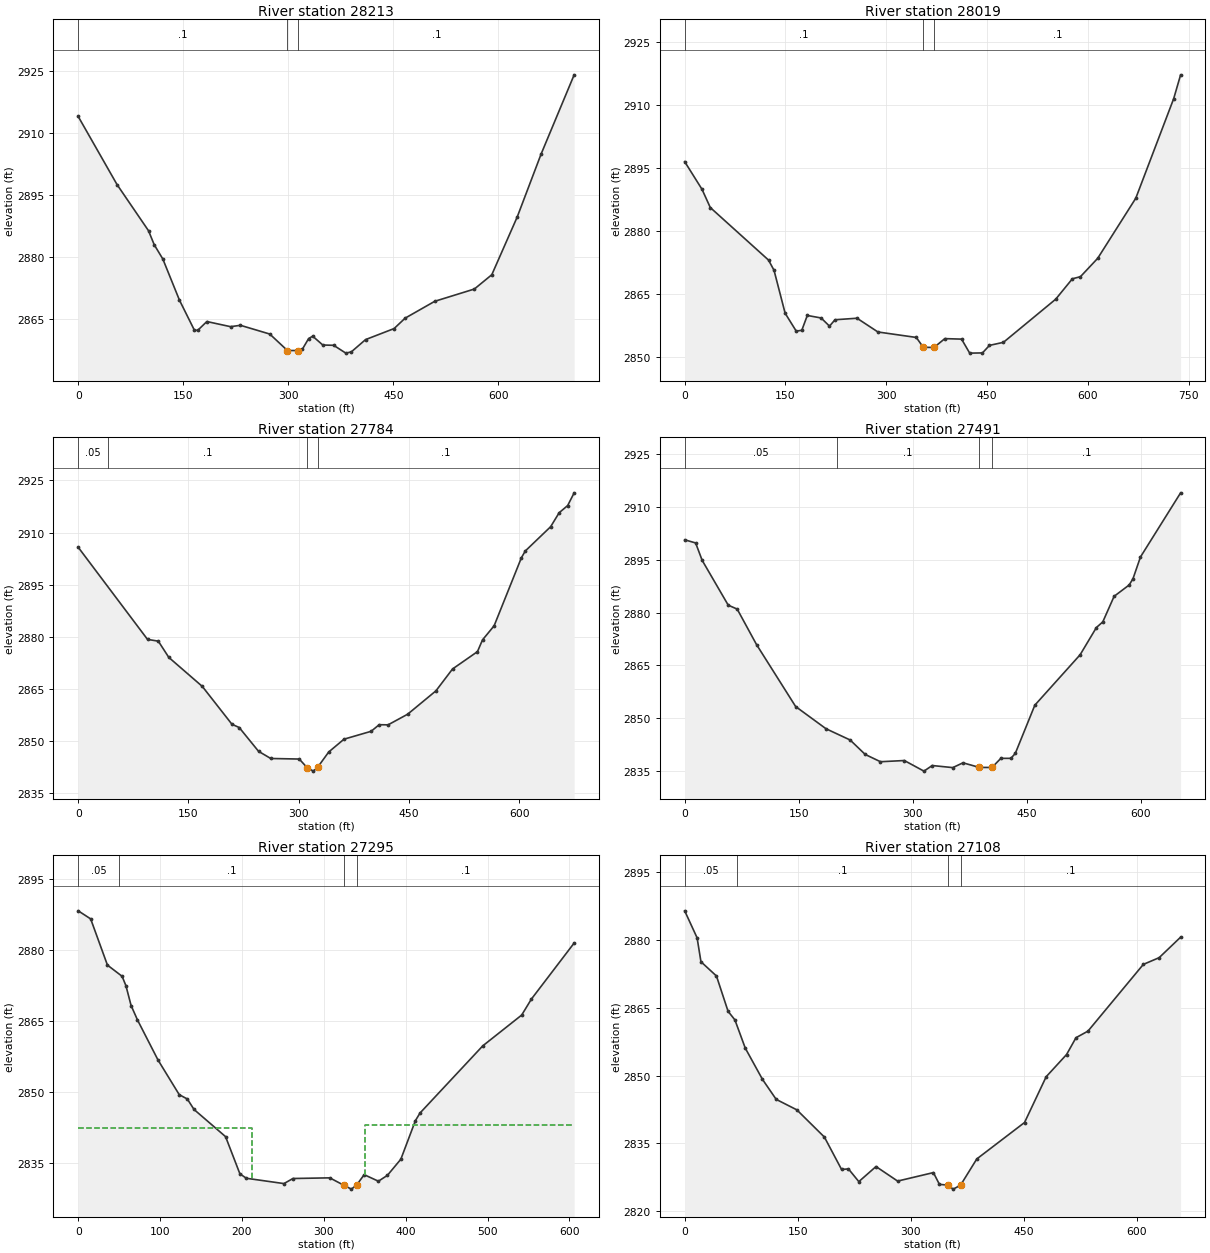
Type RM Length L Ch R = 1 ,28213   ,193.9,193.9,191.9
XS GIS Cut Line= 3
2234817.85997518615680.8449162382234979.92867924615714.043473797
2235441.33320807615428.389846962
#Sta/Elev= 30
       0 2914.02    55.4 2897.58   100.4 2886.42   108.5 2883.05   120.8  2879.6
   144.6 2869.64   165.7 2862.46   170.4 2862.33   183.7 2864.49   217.5 2863.25
   231.6 2863.58   273.5 2861.47  298.752857.485   314.4 2857.49   320.2 2857.85
     329 2860.38   334.8 2860.95   349.2 2858.82   364.7 2858.75   382.1 2856.86
     390 2857.17   410.3 2860.13     451 2862.79   466.8 2865.31   509.1 2869.38
   565.6 2872.34   590.5 2875.79   626.8 2889.74     661 2904.98   708.1 2924.08
#Mann= 3 ,-1,0
       0      .1       0  298.75    .045       0   314.4      .1       0
Bank Sta=298.75,314.4
XS Rating Curve= 0 ,0
Exp/Cntr=0.3,0.1

Type RM Length L Ch R = 1 ,28019   ,240.6,235.8,231.3
XS GIS Cut Line= 3
2235079.58926256616086.1637490142235139.43601205615848.394230765
2235519.54374531615534.603165864
#Sta/Elev= 30
       0 2896.46    25.8 2889.88    38.1 2885.55   124.8 2873.05     133 2870.61
   149.5 2860.41     166 2856.16   174.3 2856.35   182.5 2859.88   203.1 2859.28
   215.5 2857.34   223.8 2858.86   256.5 2859.22   287.6 2855.95   344.7 2854.65
   355.1 2852.31     3712852.264   387.2 2854.37   412.1 2854.25   424.2 2850.92
   443.2 2850.97   453.6 2852.76   474.4 2853.49   552.2 2863.75     577  2868.6
     589  2869.1   614.7 2873.47   671.4 2887.77   727.8 2911.45   738.1 2917.11
#Mann= 3 ,-1,0
       0      .1       0   355.1    .045       0     371      .1       0
Bank Sta=355.1,371
XS Rating Curve= 0 ,0
Exp/Cntr(USF)=0,0
Exp/Cntr=0.3,0.1

Type RM Length L Ch R = 1 ,27784   ,289.7,292.4,295.5
XS GIS Cut Line= 4
 2235292.2946634616181.3094465222235405.11574215 615975.30548212
2235444.96464919615832.5572689832235656.11948323615631.073837531
#Sta/Elev= 30
       0 2905.76    94.3 2879.23     109 2878.72   123.3 2874.04   168.9 2865.68
   209.2 2854.79   219.1 2853.85   245.4    2847     262 2844.93   300.8 2844.77
   311.4 2842.32   319.9 2841.29   325.82842.391   340.9  2846.8   361.7 2850.49
   398.6 2852.76   409.6 2854.66   421.7 2854.62   448.3 2857.68   486.8 2864.41
   509.4 2870.71   543.3  2875.7   550.2 2879.09     566 2883.15   603.1 2902.74
   608.4 2904.69   642.9 2911.68   654.5 2915.71   666.1 2917.78   674.9 2921.44
#Mann= 4 ,-1,0
       0     .05       0      40      .1       0   311.4    .045       0
   325.8      .1       0
Bank Sta=311.4,325.8
XS Rating Curve= 0 ,0
Exp/Cntr=0.3,0.1

Type RM Length L Ch R = 1 ,27491   ,193.4,196.4,196.6
XS GIS Cut Line= 2
2235467.22449581 616308.323151012235853.80214793615782.642243316
#Sta/Elev= 30
       0 2900.65    14.4 2899.76      23 2894.82    57.3 2882.09    69.1 2880.97
    94.5 2870.91     146  2853.3     186 2846.99   217.7  2843.8   237.5  2839.7
   257.6 2837.63     289 2837.97   314.8 2834.96   325.7 2836.55   352.7 2835.96
   366.2 2837.32  387.74 2836.01   404.3    2836     416 2838.59   429.2 2838.59
     435    2840   460.7 2853.69   520.3 2868.01   541.7 2875.74   550.1 2877.34
     565  2884.6   584.8 2887.82   589.8 2889.58   599.7 2895.78   652.5 2913.99
#Mann= 4 ,-1,0
       0     .05       0     200      .1       0  387.74    .045       0
   404.3      .1       0
Bank Sta=387.74,404.3
XS Rating Curve= 0 ,0
Exp/Cntr(USF)=0,0
Exp/Cntr=0.3,0.1

Type RM Length L Ch R = 1 ,27295   ,186.9,186.5,185
XS GIS Cut Line= 4
2235549.13786914616356.5439044272235838.18724936616084.546269298
2235896.12709561616019.3001964492235979.02008624 615930.25265486
#Sta/Elev= 30
       0 2888.26    15.2 2886.56    35.7 2876.81    53.6 2874.45    58.3 2872.46
    64.6 2868.28    72.4 2865.24    97.5 2856.78   123.4 2849.48   133.3 2848.56
   141.5 2846.35     180 2840.62   197.5 2832.78   205.4 2831.84   251.3 2830.72
   262.3 2831.79   307.3 2831.93   324.3 2830.38   333.7 2829.55  340.192830.431
   349.3  2832.6   366.7 2831.22   377.7 2832.46   394.1 2835.86   411.9    2844
   417.5  2845.6   494.2 2859.78   541.7 2866.27   553.6 2869.65   605.8 2881.47
#Mann= 4 ,-1,0
       0     .05       0      50      .1       0   324.3    .045       0
  340.19      .1       0
#XS Ineff= 2 , 0
          212.78 2842.45  349.75         2843.17
Permanent Ineff=
       F       F
Bank Sta=324.3,340.19
XS Rating Curve= 0 ,0
Exp/Cntr(USF)=0,0
Exp/Cntr=0.3,0.1

Type RM Length L Ch R = 1 ,27108   ,231.4,233.8,236.7
XS GIS Cut Line= 3
2235621.74306397616460.1215398782235849.36825366616334.646478708
2236108.06889438616031.505362032
#Sta/Elev= 30
       0 2886.46    16.5 2880.48    21.6 2875.19    42.2 2872.03    57.6 2864.22
    66.7 2862.31    80.4 2856.08   103.3 2849.14   121.5 2844.72   148.9  2842.4
   185.5 2836.37   208.3  2829.2   217.4 2829.33   231.2 2826.51     254 2829.85
   282.7 2826.63   330.2 2828.51   338.2  2825.9     3492825.751   356.5 2824.85
   366.22825.716   387.8 2831.53   451.2  2839.6   479.9 2849.73     507 2854.65
   519.5 2858.37   535.4 2859.83   608.9  2874.6   629.9 2876.09   658.4 2880.63
#Mann= 4 ,-1,0
       0     .05       0      70      .1       0     349    .045       0
   366.2      .1       0
Bank Sta=349,366.2
XS Rating Curve= 0 ,0
Exp/Cntr(USF)=0,0
Exp/Cntr=0.3,0.1

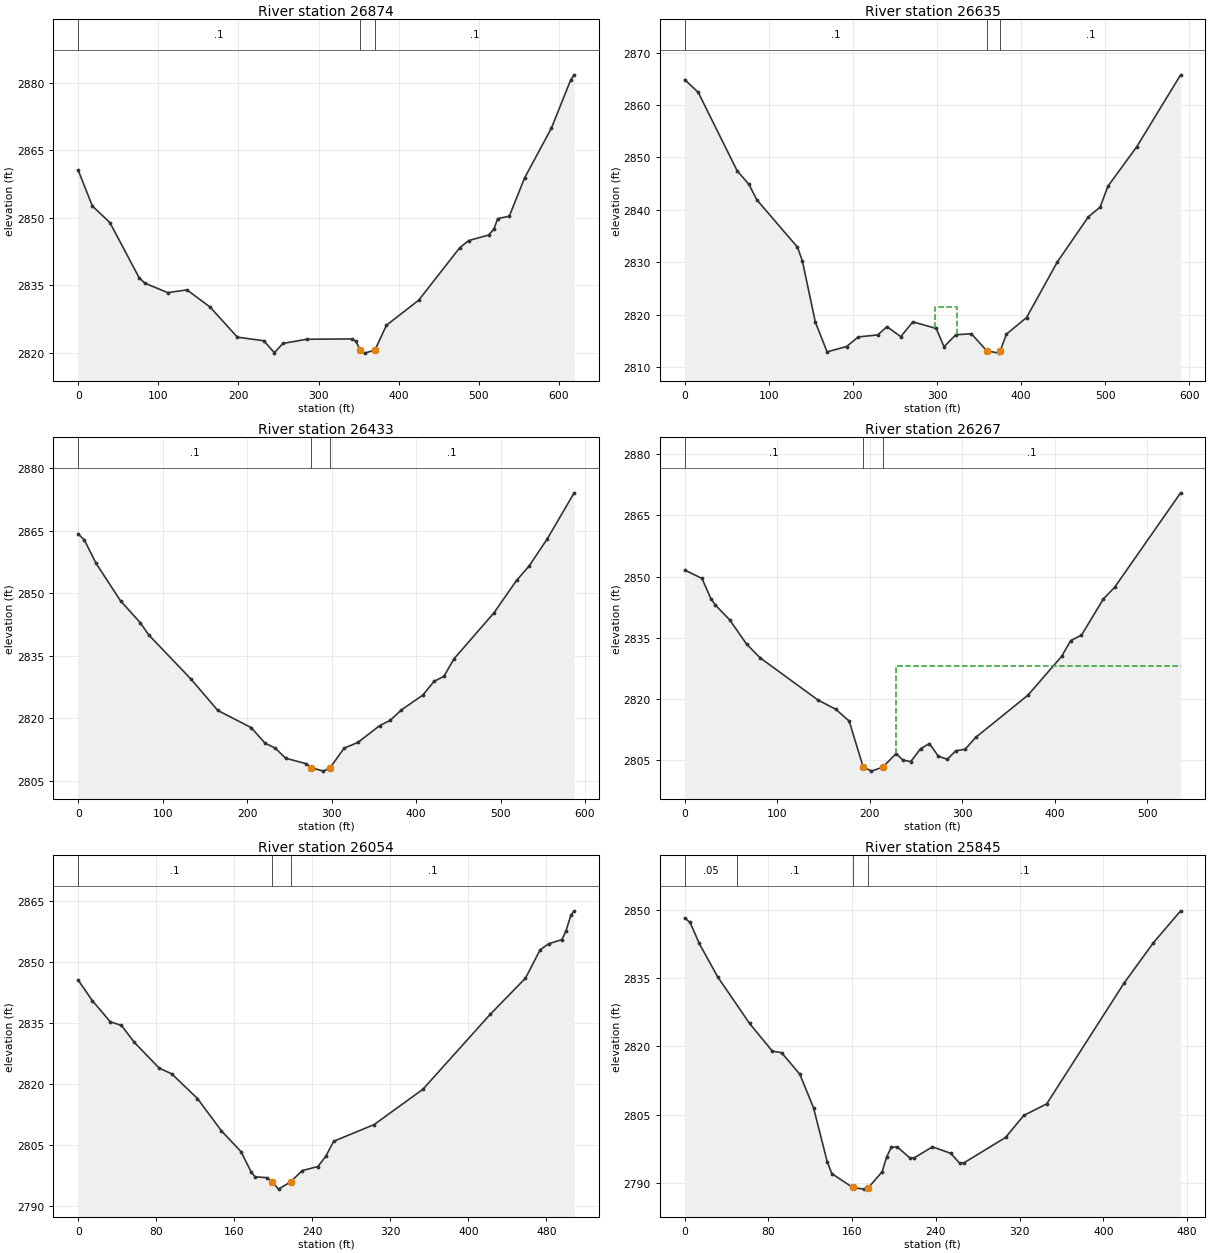
Type RM Length L Ch R = 1 ,26874   ,237.9,239.3,238.7
XS GIS Cut Line= 2
2235794.75237305616602.9261666162236311.83706693616262.548286887
#Sta/Elev= 30
       0 2860.53    17.7 2852.58    39.6  2848.9    75.9  2836.7    83.1 2835.45
   111.8 2833.34   135.8 2833.95   164.5 2830.15   198.7 2823.45   231.6 2822.65
   244.9 2819.99   255.5 2822.05   285.3 2822.98   341.7 2823.06   346.5 2822.56
  351.962820.572   357.5  2819.9   370.4 2820.57   384.8  2826.1   425.1 2831.67
     476 2843.26   487.4 2844.91   512.4 2846.14   518.9 2847.46   523.7  2849.8
   538.1  2850.3   557.2 2858.81   590.7 2869.89   614.7 2880.55   619.1 2881.73
#Mann= 3 ,-1,0
       0      .1       0  351.96    .045       0   370.4      .1       0
Bank Sta=351.96,370.4
XS Rating Curve= 0 ,0
Exp/Cntr(USF)=0,0
Exp/Cntr=0.3,0.1

Type RM Length L Ch R = 1 ,26635   ,197.7,201.8,203.6
XS GIS Cut Line= 2
2235906.28044428 616786.875063322236414.67463911616488.501262366
#Sta/Elev= 30
       0 2864.86    16.1 2862.42    62.5 2847.41    76.4 2844.86    85.7 2841.91
   134.1 2832.86     140 2830.17   155.3 2818.56   169.3 2812.87   192.4 2813.89
   206.3 2815.72   229.5 2816.11   240.4 2817.69   256.9 2815.77   271.2 2818.61
     299 2817.34   308.3 2813.84   322.2 2816.13   340.8 2816.33     359 2813.08
   373.2 2812.63  375.02 2813.05   382.5 2816.26   406.4 2819.43   442.8    2830
   479.9 2838.67   493.8  2840.5   503.1  2844.5   537.5 2852.07   589.5 2865.77
#Mann= 3 ,-1,0
       0      .1       0     359    .045       0  375.02      .1       0
#XS Ineff= 1 ,-1
  297.18  323.612821.384
Permanent Ineff=
       F
Bank Sta=359,375.02
XS Rating Curve= 0 ,0
Exp/Cntr(USF)=0,0
Exp/Cntr=0.3,0.1

Type RM Length L Ch R = 1 ,26433   ,169.9,166.3,161.6
XS GIS Cut Line= 4
2236004.77276692616903.7855218262236164.09858297616811.086865219
2236329.21806505616779.221702011 2236536.3416259 616669.14204729
#Sta/Elev= 30
       0 2864.27     7.3 2862.77    21.1  2857.2    50.2 2848.15    73.4 2842.94
    83.4 2840.01   133.5 2829.38   165.3 2821.84   204.8 2817.72   221.1 2814.01
   233.3 2812.79   245.5 2810.38     270 2809.05  276.062808.069   290.3 2807.27
   298.1 2808.07   314.8 2812.79   331.1 2814.16   356.8  2818.2   369.4 2819.48
   382.4 2821.95     408 2825.54   421.3 2828.85   432.9 2830.04   444.9 2834.26
   492.3 2845.33   518.9 2853.07   533.7 2856.52   555.2 2863.04   587.1 2874.12
#Mann= 3 ,-1,0
       0      .1       0  276.06    .045       0   298.1      .1       0
Bank Sta=276.06,298.1
XS Rating Curve= 0 ,0
Exp/Cntr(USF)=0,0
Exp/Cntr=0.3,0.1

Type RM Length L Ch R = 1 ,26267   ,207.6,213.3,216.7
XS GIS Cut Line= 2
2236124.67596931617061.0825793922236569.33983772616761.260361928
#Sta/Elev= 30
       0 2851.62    18.7 2849.55    28.3 2844.63    33.2 2843.03    48.6 2839.42
    66.9 2833.47    81.4 2830.12   144.1 2819.75   163.4 2817.47   177.9 2814.59
     193 2803.32     202 2802.31  214.16  2803.3   228.8 2806.62   235.8 2805.03
   244.5 2804.65   255.1 2807.82   264.6 2809.06   274.4 2805.96     284 2805.22
   293.2  2807.3   303.3 2807.67   314.6 2810.56   371.3 2820.95   407.7 2830.47
   417.4  2834.3   429.1 2835.65   452.9 2844.57   464.9 2847.36   536.3 2870.54
#Mann= 3 ,-1,0
       0      .1       0     193    .045       0  214.16      .1       0
#XS Ineff= 2 , 0
                          228.74            2828
Permanent Ineff=
       F       F
Bank Sta=193,214.16
XS Rating Curve= 0 ,0
Exp/Cntr(USF)=0,0
Exp/Cntr=0.3,0.1

Type RM Length L Ch R = 1 ,26054   ,210.7,208.3,205.6
XS GIS Cut Line= 4
 2236223.0491349617178.8165707872236381.91062503617115.676392008
2236475.03302554617104.7483194792236687.12178454616984.583916865
#Sta/Elev= 30
       0 2845.48    14.4 2840.48    32.9 2835.25    44.3 2834.38    57.6  2830.2
      83 2823.91    95.9  2822.5   122.3 2816.44   146.9 2808.51   166.9 2803.44
   177.3 2798.45   181.3 2797.25   193.3 2797.04   198.82796.052   205.4 2794.23
     2182796.045   229.6 2798.77   245.7 2799.77   253.8 2802.25   261.9 2805.96
   303.4 2810.06   353.4 2818.71   422.3 2837.06   458.6 2845.96   473.6  2852.9
   482.4  2854.4   495.9 2855.41     500 2857.46   505.1 2861.38   508.5 2862.47
#Mann= 3 ,-1,0
       0      .1       0   198.8    .045       0     218      .1       0
Bank Sta=198.8,218
XS Rating Curve= 0 ,0
Exp/Cntr(USF)=0,0
Exp/Cntr=0.3,0.1

Type RM Length L Ch R = 1 ,25845   ,193.7,190.2,186.5
XS GIS Cut Line= 3
2236323.43116415 617372.060123222236655.01450593617226.486948782
2236750.44580917617168.257679006
#Sta/Elev= 30
       0 2848.18     5.2 2847.19    13.9 2842.59    31.4  2835.3      62 2825.01
    83.8 2818.92    92.6 2818.59     110 2813.86   123.1 2806.51   136.2 2794.64
   140.6 2792.01   160.6 2788.98   171.2 2788.61   175.6 2788.96   188.7 2792.43
     193 2795.69   197.4 2797.79   203.1 2797.91   214.9 2795.51   219.2 2795.46
   236.7  2797.9   254.2 2796.48   262.9 2794.28   266.9 2794.39   306.6 2799.96
   324.1 2804.81   345.9 2807.33   419.7 2833.82   447.8 2842.71   473.9 2849.75
#Mann= 4 ,-1,0
       0     .05       0      50      .1       0   160.6    .045       0
   175.6      .1       0
Bank Sta=160.6,175.6
XS Rating Curve= 0 ,0
Exp/Cntr(USF)=0,0
Exp/Cntr=0.3,0.1

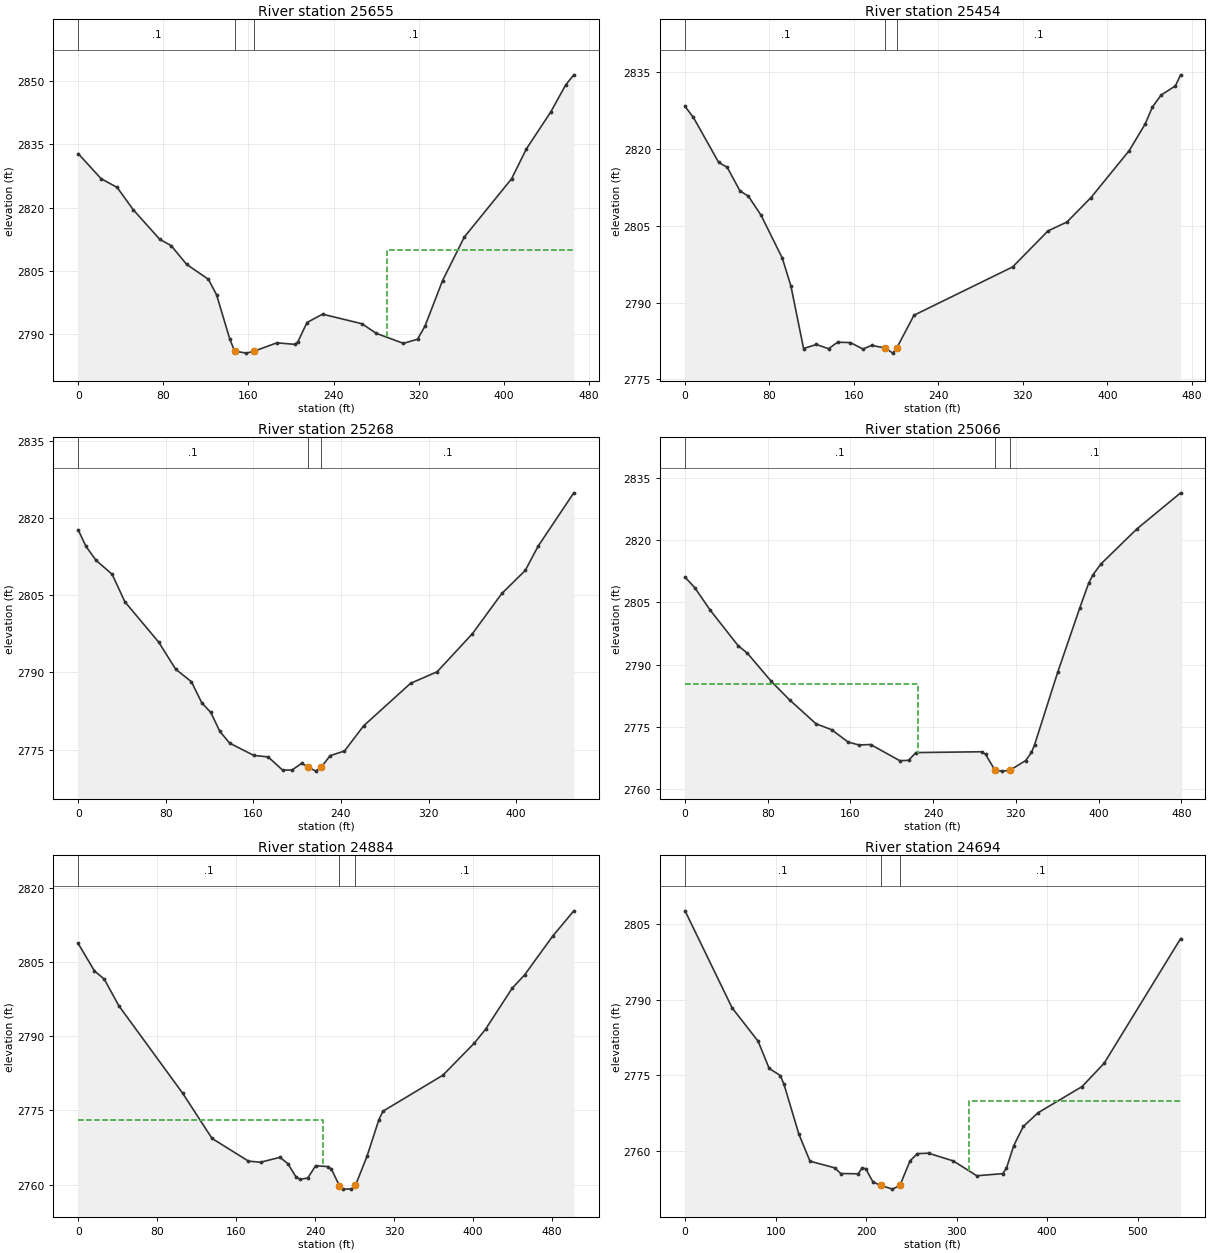
Type RM Length L Ch R = 1 ,25655   ,195.9,200.8,203.7
XS GIS Cut Line= 4
2236462.90690887617558.1568546212236558.06787355617486.460237402
2236707.97898228617320.9062303672236814.87212068617259.638212016
#Sta/Elev= 30
       0 2832.81    21.6 2826.84    36.6 2824.79    51.7 2819.49    76.7 2812.44
    87.3 2810.98   101.8 2806.53   122.3 2802.97     130 2799.31   142.5 2788.72
     147 2785.92     158 2785.43  165.322785.889   186.7 2787.88   203.7 2787.51
   206.5 2788.15     215  2792.7   229.6 2794.68   266.6 2792.41   280.1 2790.13
   305.6 2787.75   318.9 2788.73   325.9 2791.86   342.4 2802.67   362.9 2813.02
   407.3 2826.85   421.1 2833.91   444.1 2842.72     458 2849.09   465.7 2851.52
#Mann= 3 ,-1,0
       0      .1       0     147    .045       0  165.32      .1       0
#XS Ineff= 2 , 0
                          290.61         2809.93
Permanent Ineff=
       F       F
Bank Sta=147,165.32
XS Rating Curve= 0 ,0
Exp/Cntr(USF)=0,0
Exp/Cntr=0.3,0.1

Type RM Length L Ch R = 1 ,25454   ,192.6,186.1,180.6
XS GIS Cut Line= 3
 2236512.4427535617607.6926992462236737.96120403617584.228351792
2236930.89028309617436.924392777
#Sta/Elev= 30
       0 2828.26     7.8 2826.17    31.9 2817.33    39.9 2816.41      52  2811.8
    60.1 2810.73    72.1    2807    92.2 2798.63   100.3 2793.21   112.3 2781.02
   124.4 2781.81     136 2780.98   144.5 2782.25   156.6 2782.18   168.6 2780.92
   176.7 2781.63   189.9 2781.11   196.8 2780.12  200.592781.134   216.9 2787.52
   310.4 2796.95   343.8 2803.97   361.8 2805.71   384.6 2810.49   420.8 2819.66
   435.9 2824.84   442.7 2828.13     451  2830.5   464.5 2832.27   469.5 2834.44
#Mann= 3 ,-1,0
       0      .1       0   189.9    .045       0  200.59      .1       0
Bank Sta=189.9,200.59
XS Rating Curve= 0 ,0
Exp/Cntr(USF)=0,0
Exp/Cntr=0.3,0.1

Type RM Length L Ch R = 1 ,25268   ,200,202.6,206
XS GIS Cut Line= 4
2236682.20560659617873.986532369 2236794.3897107617802.212129369
2236849.38402104617674.4312318062236969.90761775617540.389062585
#Sta/Elev= 30
       0 2817.72     7.1 2814.52    16.3  2811.8      31  2809.1    42.6 2803.75
    73.6 2795.88    88.9 2790.67   103.4 2788.21   112.8 2784.13   121.1 2782.23
   129.4 2778.54   138.4 2776.26   160.4 2773.88   173.5 2773.59   186.6 2771.04
   195.3 2771.05     204 2772.34  209.66 2771.67     217 2770.83  222.16 2771.66
   230.1 2773.84   243.2 2774.74   260.6 2779.62   303.5 2787.89   327.8 2790.14
     360 2797.54   386.9 2805.36   408.3 2809.84     420 2814.54   452.6 2824.92
#Mann= 3 ,-1,0
       0      .1       0  209.66    .045       0  222.16      .1       0
Bank Sta=209.66,222.16
XS Rating Curve= 0 ,0
Exp/Cntr(USF)=0,0
Exp/Cntr=0.3,0.1

Type RM Length L Ch R = 1 ,25066   ,177,181.7,187.4
XS GIS Cut Line= 3
2236758.81840176617980.515108787 2236886.5687379617912.729216143
 2237131.6408113617684.603615899
#Sta/Elev= 30
       0 2811.06     9.4 2808.53    24.2 2803.15    51.3 2794.56    60.4  2792.7
    83.3 2785.97   101.1 2781.48   126.6 2775.73   141.9 2774.27   157.7 2771.32
   168.1 2770.61   179.6 2770.71   207.7 2766.82   216.2  2766.9   223.3 2768.77
     287 2768.97   290.7 2768.35   299.8 2764.52   306.8  2764.3   314.2  2764.5
   329.4 2766.83   335.1  2768.8   338.1 2770.64   360.5 2788.15   381.8 2803.62
   390.5 2809.66   394.5  2811.6   402.3 2814.24     437 2822.67   479.4 2831.39
#Mann= 3 ,-1,0
       0      .1       0   299.8    .045       0   314.2      .1       0
#XS Ineff= 2 , 0
          224.91 2785.38
Permanent Ineff=
       F       F
Bank Sta=299.8,314.2
XS Rating Curve= 0 ,0
Exp/Cntr(USF)=0,0
Exp/Cntr=0.3,0.1

Type RM Length L Ch R = 1 ,24884   ,191.3,190.5,189.1
XS GIS Cut Line= 4
2236796.62207266618026.1402288362236937.40815738617975.300809353
2237110.78361357617966.1757853432237235.92679999617838.425449207
#Sta/Elev= 30
       0 2808.76    16.5  2803.2    26.4 2801.56      41 2796.22   105.8  2778.5
   135.6 2769.35   172.5 2764.76   184.8 2764.54   204.5 2765.53   212.5 2764.23
   220.5 2761.61   224.6 2761.08   232.6 2761.35   240.6 2763.84   252.6 2763.66
   256.6 2763.12   264.6 2759.81   268.6  2759.1   276.6 2759.12  280.942759.873
   292.6 2765.74   304.7 2773.17   308.7 2774.84   369.5 2782.13   401.4 2788.63
   412.7 2791.42   439.6 2799.69   452.3 2802.42   480.6 2810.21   502.1 2815.36
#Mann= 3 ,-1,0
       0      .1       0   264.6    .045       0  280.94      .1       0
#XS Ineff= 2 , 0
           247.8 2773.17
Permanent Ineff=
       F       F
Bank Sta=264.6,280.94
XS Rating Curve= 0 ,0
Exp/Cntr(USF)=0,0
Exp/Cntr=0.3,0.1

Type RM Length L Ch R = 1 ,24694   ,265.2,265.5,263.6
XS GIS Cut Line= 3
2236889.35957317618199.0120310992237254.36053356618119.493964728
 2237337.7893245617966.975706279
#Sta/Elev= 30
       0 2807.59      52 2788.36    80.7 2781.76    92.9 2776.37   105.2 2774.96
   109.3 2773.21   125.7 2763.36     138 2757.99   165.3 2756.67     172 2755.54
   191.2 2755.49   195.3 2756.57   199.4 2756.53   207.6 2753.87   215.9  2753.2
   229.1 2752.45   237.42753.206   248.5 2758.06   256.7 2759.49     269 2759.57
   296.4 2758.03   322.2  2755.1   350.9 2755.52     355 2756.59   363.1 2761.09
   373.6 2764.87   389.9 2767.58   438.5 2772.77   462.8 2777.36   547.4  2802.1
#Mann= 3 ,-1,0
       0      .1       0   215.9    .045       0   237.4      .1       0
#XS Ineff= 2 , 0
                          313.65         2769.97
Permanent Ineff=
       F       F
Bank Sta=215.9,237.4
XS Rating Curve= 0 ,0
Exp/Cntr(USF)=0,0
Exp/Cntr=0.3,0.1

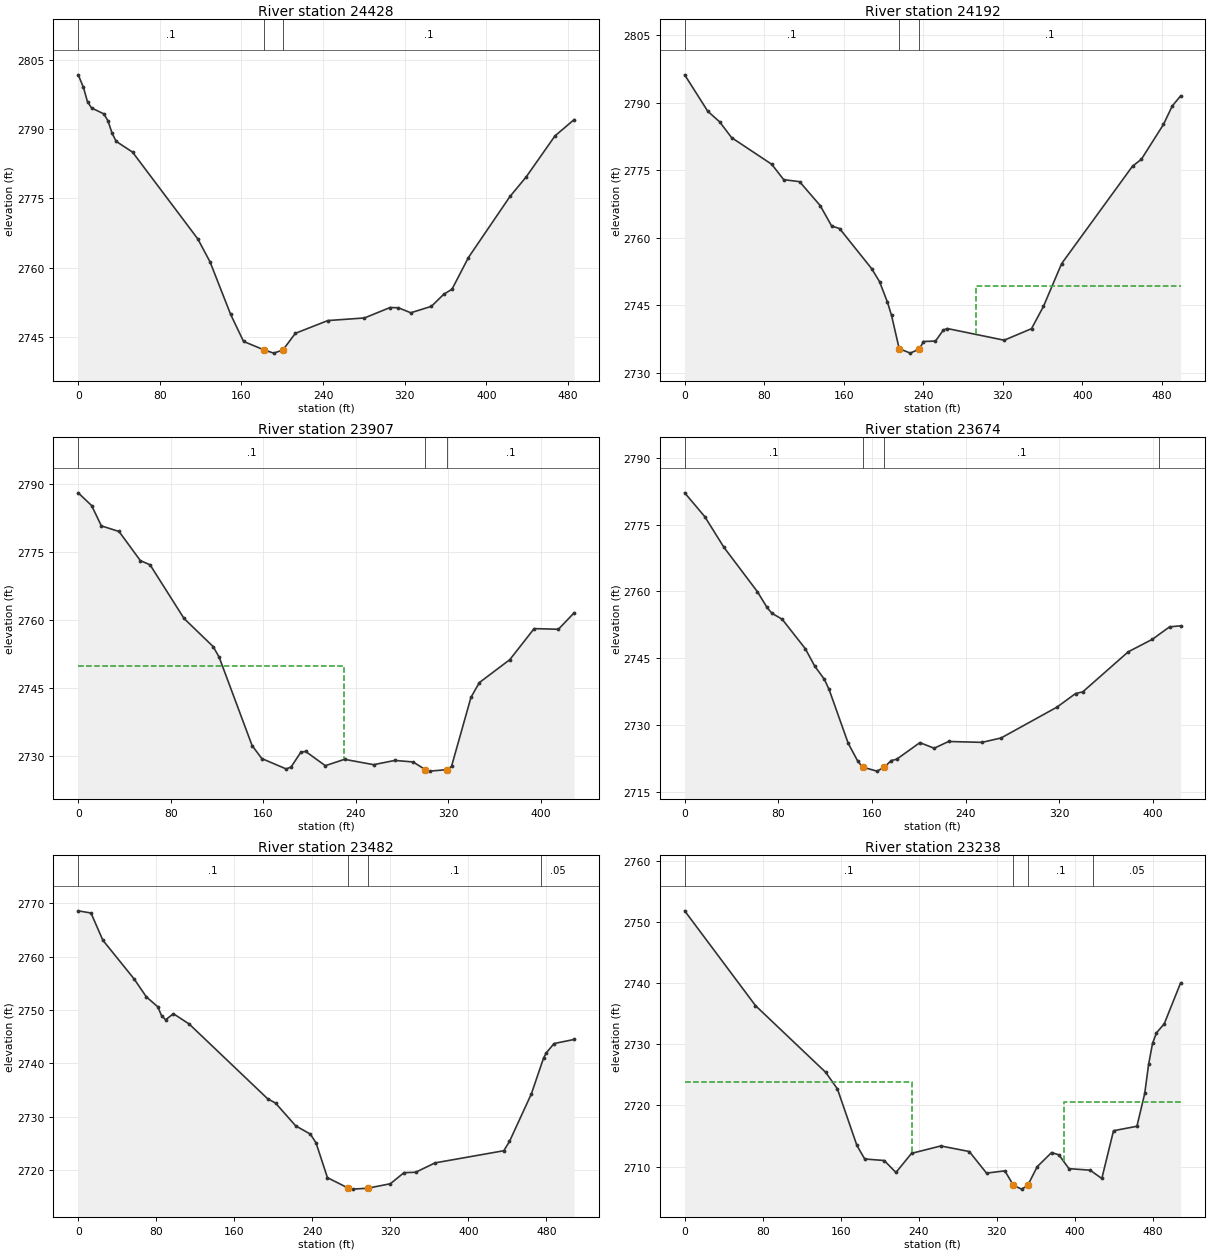
Type RM Length L Ch R = 1 ,24428   ,233.5,236,237.9
XS GIS Cut Line= 4
2236955.03011934618396.539174209 2237101.1514944618399.391675154
2237248.54433352618348.6885384972237430.71051055618374.200641405
#Sta/Elev= 30
       0 2801.72     5.1 2799.02     9.1 2795.89    13.1 2794.56    25.1 2793.28
    29.2 2791.77    33.2 2789.09    37.2 2787.34    53.2 2785.03   117.2 2766.26
   129.2 2761.29   149.3 2749.99     162 2744.11182.05242742.282   191.6 2741.58
   200.6 2742.26   212.8 2745.86   244.7 2748.62   280.5 2749.18   305.7 2751.44
   313.8 2751.38   325.9  2750.3   346.1 2751.69   358.2  2754.3   366.3 2755.39
   382.4 2762.24   423.1 2775.43     439 2779.66   467.2 2788.52     486 2792.05
#Mann= 3 ,-1,0
       0      .1       0182.0524    .045       0   200.6      .1       0
Bank Sta=182.0524,200.6
XS Rating Curve= 0 ,0
Exp/Cntr(USF)=0,0
Exp/Cntr=0.3,0.1

Type RM Length L Ch R = 1 ,24192   ,281.5,285.1,289
XS GIS Cut Line= 3
2236953.05105568618637.5168374892237223.44981099618611.838190378
2237427.67732887618512.189965521
#Sta/Elev= 30
       0 2796.17    23.2 2788.09    35.3  2785.7    47.2 2782.22    87.6  2776.3
    99.6 2772.89   115.6 2772.44   136.3 2767.14   147.8 2762.61   155.8 2762.03
     188 2753.15     196 2750.25     204 2745.67   208.1 2742.72  215.792735.349
     227 2734.36   236.2  2735.3   240.2 2736.94   252.3 2737.04   260.3 2739.51
   264.3 2739.82   321.4 2737.23   348.9 2739.79   360.9 2744.73   379.2 2754.24
   450.5 2775.88   459.4 2777.41   481.6 2785.14   490.5 2789.25   498.9  2791.5
#Mann= 3 ,-1,0
       0      .1       0  215.79    .045       0   236.2      .1       0
#XS Ineff= 2 , 0
                          293.31         2749.31
Permanent Ineff=
       F       F
Bank Sta=215.79,236.2
XS Rating Curve= 0 ,0
Exp/Cntr(USF)=0,0
Exp/Cntr=0.3,0.1

Type RM Length L Ch R = 1 ,23907   ,231.6,233.4,230
XS GIS Cut Line= 2
 2237009.1047746618771.7850479192237417.12370532618903.446108631
#Sta/Elev= 30
       0 2788.05    11.6 2785.24      20 2780.77    35.3 2779.53    53.7 2773.12
    62.1 2772.19    91.5 2760.36   116.7 2754.16   121.8 2751.85   150.3 2732.37
   158.7  2729.5   179.8 2727.21     184 2727.64   192.4 2730.89   196.6 2731.07
   213.6 2727.93   230.2 2729.33   255.4 2728.15   273.7 2729.09   289.5 2728.75
  299.942727.076   304.1 2726.73   319.1 2727.07   322.7 2727.78   339.5 2742.98
   346.7 2746.23   373.1  2751.3   394.1 2758.13   415.1 2757.99   428.7 2761.62
#Mann= 3 ,-1,0
       0      .1       0  299.94    .045       0   319.1      .1       0
#XS Ineff= 2 , 0
             230    2750
Permanent Ineff=
       F       F
Bank Sta=299.94,319.1
XS Rating Curve= 0 ,0
Exp/Cntr(USF)=0,0
Exp/Cntr=0.3,0.1

Type RM Length L Ch R = 1 ,23674   ,197.6,191.7,183.7
XS GIS Cut Line= 3
 2236971.3011037618968.6248515582237241.14109942619023.374995616
2237376.71288471618963.410552124
#Sta/Elev= 30
       0 2782.13    17.2 2776.77    33.5  2769.9    62.1 2759.93    70.3  2756.4
    74.4  2755.1    83.3 2753.73     103 2747.13   111.1  2743.2   119.3 2740.25
   123.3 2737.99   139.7 2725.86   147.8 2721.88   151.9 2720.53   164.2 2719.62
   170.42720.467   176.4    2722     181 2722.28   200.9 2726.02   213.1 2724.76
   225.4 2726.28   253.9 2726.08   270.3 2727.07     318    2734   333.9 2737.05
     340 2737.42   378.9 2746.43   399.4 2749.22   414.2 2752.03   423.6 2752.26
#Mann= 4 ,-1,0
       0      .1       0   151.9    .045       0   170.4      .1       0
  405.34     .05       0
Bank Sta=151.9,170.4
XS Rating Curve= 0 ,0
Exp/Cntr(USF)=0,0
Exp/Cntr=0.3,0.1

Type RM Length L Ch R = 1 ,23482   ,234.6,244,250.7
XS GIS Cut Line= 3
2236919.15810936619181.1075534992237142.06941017619205.875475812
2237385.83790872619059.875091655
#Sta/Elev= 30
       0 2768.57    13.1 2768.16    25.2 2763.08    57.4 2755.78    69.8 2752.45
    81.5 2750.59    85.5  2748.9    89.6 2748.15    97.6 2749.28   113.7 2747.36
   194.2 2733.34   202.3 2732.53   222.9 2728.27     238 2726.71   243.8 2725.07
   255.5 2718.55  276.692716.604   281.7  2716.4   296.7 2716.57     320 2717.41
     334 2719.49   345.9 2719.56   365.8 2721.32   436.3  2723.6   442.1 2725.34
   464.5 2734.24   477.1    2741     480 2741.99   487.8 2743.69   508.4 2744.46
#Mann= 4 ,-1,0
       0      .1       0  276.69    .045       0   296.7      .1       0
  474.28     .05       0
Bank Sta=276.69,296.7
XS Rating Curve= 0 ,0
Exp/Cntr(USF)=0,0
Exp/Cntr=0.3,0.1

Type RM Length L Ch R = 1 ,23238   ,271.1,267.1,261.5
BEGIN DESCRIPTION:
Structure XS 4
END DESCRIPTION:
XS GIS Cut Line= 4
2236959.56892998619334.9293868072237208.55172796619338.840111382
 2237319.4601937619406.6728253672237448.90562729619408.345505805
#Sta/Elev= 30
       0 2751.82    72.6 2736.32   144.6 2725.41   156.6  2722.7   176.6 2713.45
   184.6 2711.24   204.6 2710.99   216.6 2709.03   232.6 2712.16   262.6 2713.37
   291.8 2712.46   309.5 2708.93   328.3  2709.3  337.142706.912   345.5 2706.31
   351.7 2706.91   361.5 2709.99   376.2 2712.29   383.7 2711.92     394 2709.66
   415.7 2709.41   427.7 2708.05   439.7 2715.86   463.7 2716.59   471.7 2721.96
   475.7 2726.73   479.7 2730.14   483.7 2731.86   491.7 2733.34   508.5 2740.04
#Mann= 4 ,-1,0
       0      .1       0  337.14    .045       0   351.7      .1       0
  419.02     .05       0
#XS Ineff= 2 , 0
          232.64  2723.9  388.59         2720.59
Permanent Ineff=
       F       F
Bank Sta=337.14,351.7
XS Rating Curve= 0 ,0
Exp/Cntr(USF)=0,0
Exp/Cntr=0.3,0.1

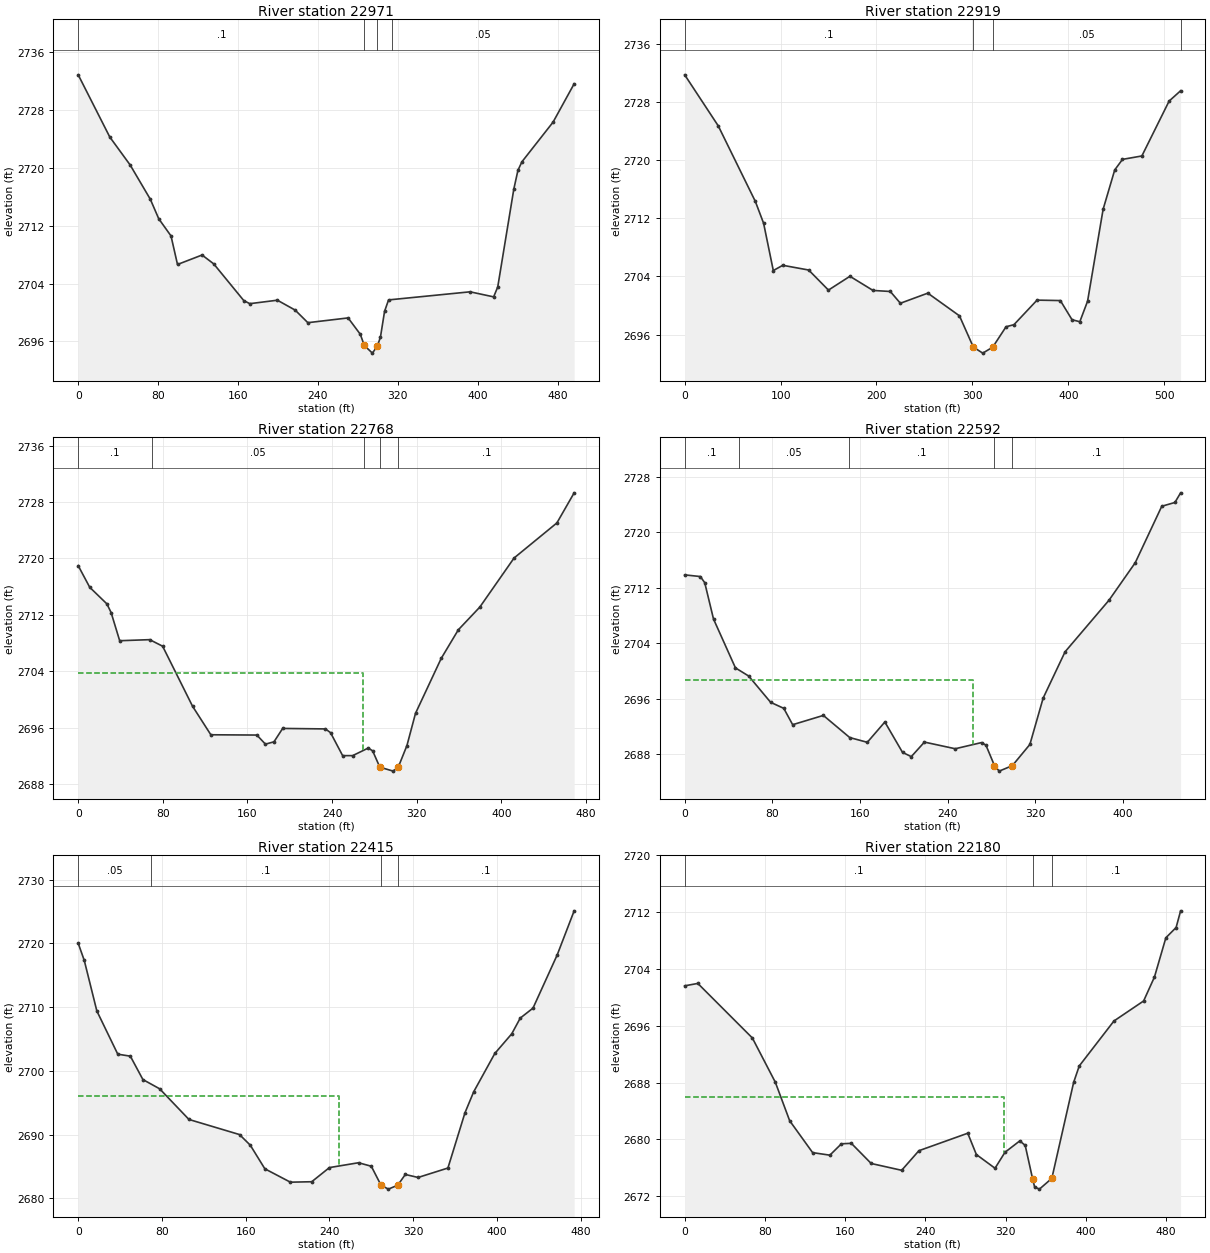
Type RM Length L Ch R = 1 ,22971   ,51.5,51.5,51.7
BEGIN DESCRIPTION:
Structure XS 3
END DESCRIPTION:
XS GIS Cut Line= 6
2236989.17391404619691.0986162722237086.60723604619710.859697162
2237102.85358226619680.6879113372237133.79900361619645.874312309
2237170.93350924619621.8916107562237439.80851649619580.805316165
#Sta/Elev= 30
       0 2732.87    31.6 2724.27      52  2720.4    72.2 2715.66    80.6 2712.97
    92.9 2710.59    99.4 2706.64     124 2707.95   135.7 2706.72   165.8 2701.64
   171.8 2701.22   199.4  2701.7   217.2 2700.33   229.9 2698.59   270.2 2699.25
   282.4 2696.99   286.4 2695.44   294.5 2694.38  299.532695.358   302.6 2696.61
   306.7 2700.16   310.7 2701.74   392.3 2702.86   415.9 2702.16     420 2703.53
   436.1 2717.07   440.2 2719.65   444.2 2720.84   475.4 2726.33   496.5 2731.63
#Mann= 4 ,-1,0
       0      .1       0   286.4    .045       0  299.53      .1       0
  314.47     .05       0
Bank Sta=286.4,299.53
XS Rating Curve= 0 ,0
Exp/Cntr(USF)=0,0
Exp/Cntr=0.3,0.1

Type RM Length L Ch R = 1 ,22919   ,151.5,151.2,151.1
BEGIN DESCRIPTION:
Structure XS 2
END DESCRIPTION:
XS GIS Cut Line= 6
2236982.05849259619728.9649517922237114.30541362619758.783294623
2237130.55175983619728.6115087982237161.49718119 619693.79790977
2237198.63168682619669.8152082172237452.03398339619630.276184694
#Sta/Elev= 30
       0 2731.73      35 2724.71    73.7 2714.31    82.3 2711.31    92.4 2704.81
   102.3 2705.53   129.3 2704.88   149.9 2702.12   172.3 2704.02   196.4 2702.07
   214.4 2701.93   224.9 2700.31   253.5  2701.7   286.5 2698.58     301 2694.27
   310.8 2693.45  321.132694.263   335.1 2697.08   343.3 2697.36   367.4 2700.74
   391.7 2700.68   403.9 2698.04     412 2697.77   420.1  2700.6   436.3 2713.24
   448.4 2718.65   456.5  2720.1   476.7 2720.57   505.1 2728.12   517.1 2729.54
#Mann= 4 ,-1,0
       0      .1       0     301    .045       0  321.13     .05       0
  517.09      .1       0
Bank Sta=301,321.13
XS Rating Curve= 0 ,0
Exp/Cntr(USF)=0,0
Exp/Cntr=0.3,0.1

Type RM Length L Ch R = 1 ,22768   ,174.3,176.6,178
BEGIN DESCRIPTION:
Structure XS 1
END DESCRIPTION:
XS GIS Cut Line= 2
 2236993.4618763619856.3593302212237456.23095108619780.751988426
#Sta/Elev= 30
       0 2718.98    10.9 2715.91    27.1 2713.56    31.1 2712.33    39.2 2708.33
    67.6 2708.48    79.8 2707.55   108.1 2699.03   125.4 2694.98   168.9 2694.94
     177 2693.65   185.1 2693.98   193.3 2695.88   233.8 2695.81   238.6 2695.27
     250 2692.02   259.5 2692.02   274.3  2693.1   278.4 2692.69  285.162690.383
   297.8 2689.82   302.7 2690.42   310.8 2693.45   318.9 2698.02   343.2 2705.82
   359.4 2709.88   379.7  2713.1   412.1 2720.07   452.6 2725.05   468.9 2729.32
#Mann= 5 ,-1,0
       0      .1       0      70     .05       0     270      .1       0
  285.16    .045       0   302.7      .1       0
#XS Ineff= 2 , 0
          269.68 2703.79
Permanent Ineff=
       F       F
Bank Sta=285.16,302.7
XS Rating Curve= 0 ,0
Exp/Cntr(USF)=0,0
Exp/Cntr=0.3,0.1

Type RM Length L Ch R = 1 ,22592   ,178.3,176.2,174.3
XS GIS Cut Line= 2
2237013.92620077619962.0113712872237465.35597509619991.715541858
#Sta/Elev= 30
       0 2713.86    14.3 2713.62    18.3 2712.73    26.3 2707.49    46.3 2700.44
    58.4 2699.26    78.4 2695.47    90.4  2694.6    98.5 2692.24   126.5 2693.58
   150.6 2690.38   166.6  2689.7   182.6 2692.63   198.7 2688.25   206.7 2687.63
   218.7 2689.73   246.8 2688.77   270.8 2689.66   274.8 2689.29   282.62686.336
   286.9 2685.54   298.9 2686.33   314.9 2689.39     327 2696.08     347 2702.76
   387.1 2710.21     411 2715.61   435.2 2723.76   447.2 2724.31   452.4  2725.7
#Mann= 5 ,-1,0
       0      .1       0      50     .05       0     150      .1       0
   282.6    .045       0   298.9      .1       0
#XS Ineff= 2 , 0
          263.18 2698.71
Permanent Ineff=
       F       F
Bank Sta=282.6,298.9
XS Rating Curve= 0 ,0
Exp/Cntr(USF)=0,0
Exp/Cntr=0.3,0.1

Type RM Length L Ch R = 1 ,22415   ,239.2,235.5,231.9
XS GIS Cut Line= 3
2236990.42357928620183.3269755262237134.31320731620183.220625254
 2237458.8381008620123.592176221
#Sta/Elev= 30
       0 2720.03     5.8 2717.33    17.8 2709.41    37.8 2702.63    49.8 2702.32
    61.8 2698.65    77.8  2697.2   105.8 2692.39   154.1 2690.02   164.4 2688.35
   178.3 2684.65   202.7 2682.55   223.1 2682.62     240 2684.84   267.8  2685.6
     280 2685.05  289.28 2682.08   296.3 2681.46   305.3 2682.08   312.5 2683.76
   324.7 2683.29   353.2 2684.77   369.5 2693.44   377.8 2696.72     398 2702.74
   414.2 2705.83   422.3 2708.29   434.5 2709.86   457.6  2718.2   473.8 2725.12
#Mann= 4 ,-1,0
       0     .05       0      70      .1       0  289.28    .045       0
   305.3      .1       0
#XS Ineff= 2 , 0
          248.74 2696.03
Permanent Ineff=
       F       F
Bank Sta=289.28,305.3
XS Rating Curve= 0 ,0
Exp/Cntr(USF)=0,0
Exp/Cntr=0.3,0.1

Type RM Length L Ch R = 1 ,22180   ,200,199.4,198.5
XS GIS Cut Line= 2
2237121.62928919620560.8841302132237522.00407039620270.541535997
#Sta/Elev= 30
       0 2701.62    13.1 2701.96    67.5 2694.28    90.4 2688.05   104.7 2682.63
   127.6 2678.14   144.8 2677.78   156.3 2679.38   166.2 2679.45     186 2676.61
   216.4 2675.65   233.6 2678.41   282.3 2680.87   290.9 2677.87   309.5 2675.94
   319.4 2678.18   334.2 2679.79   339.6 2679.16     347 2674.44     349  2673.3
   353.8    2673  366.162674.515   387.9 2688.02   393.5 2690.34   428.1 2696.67
   457.7 2699.49   468.5 2702.86   479.9 2708.39   490.1 2709.83   494.6 2712.18
#Mann= 3 ,-1,0
       0      .1       0     347    .045       0  366.16      .1       0
#XS Ineff= 2 , 0
          318.77 2686.03
Permanent Ineff=
       F       F
Bank Sta=347,366.16
XS Rating Curve= 0 ,0
Exp/Cntr(USF)=0,0
Exp/Cntr=0.3,0.1