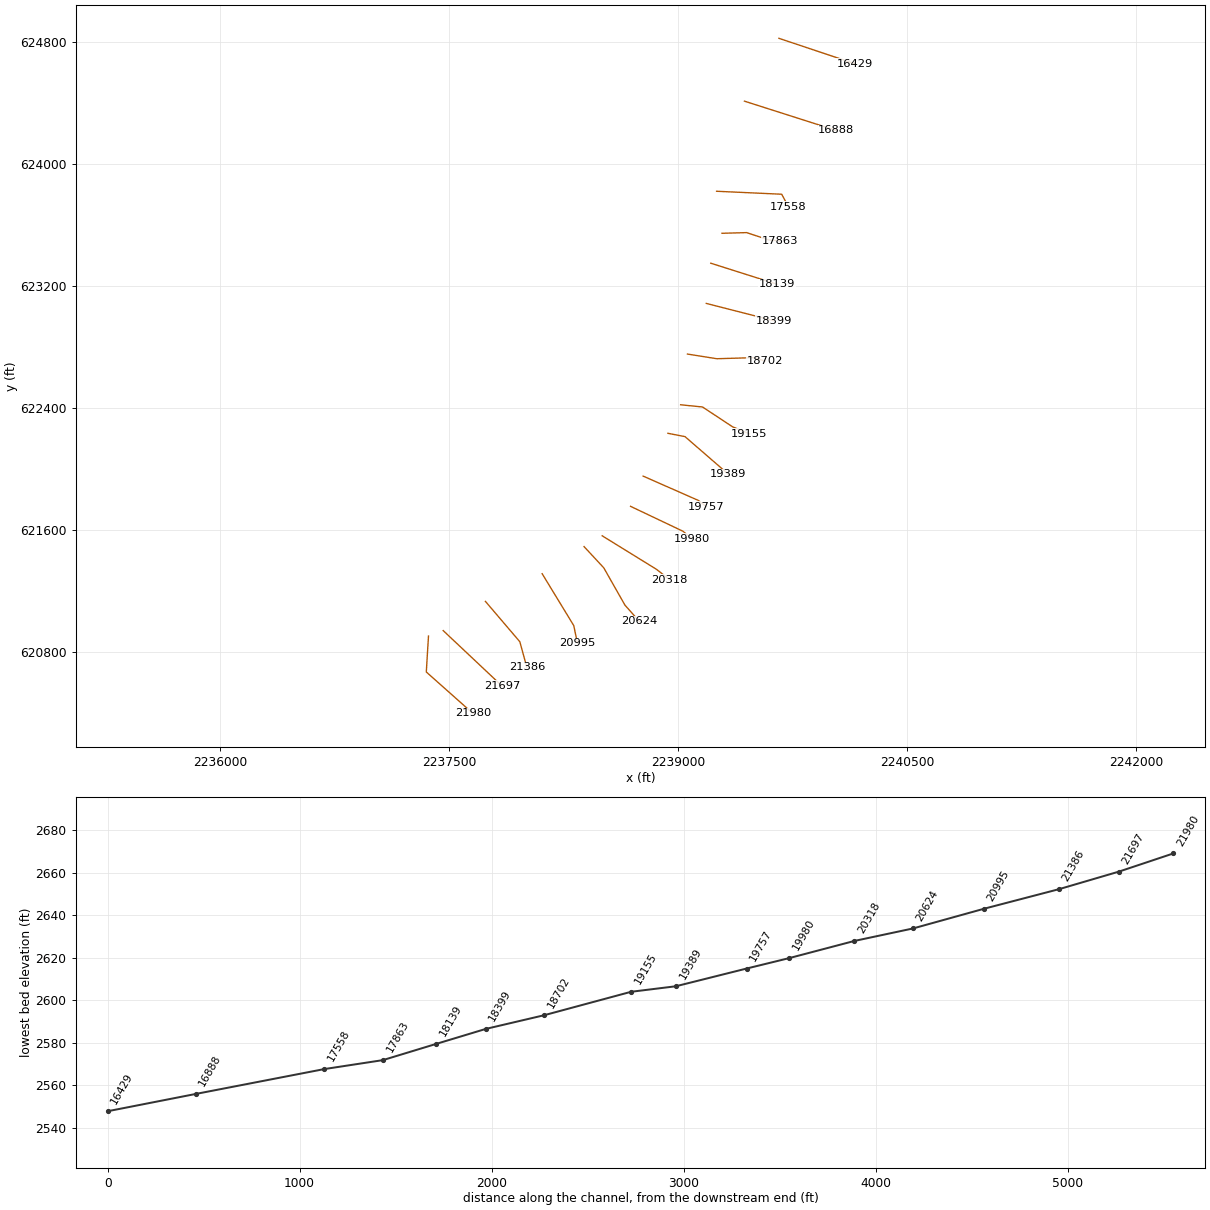
HEC-RAS study KITTLECK.prj: KITTLECK

--- KITTLECK.g01 (geometry) --- (continued)

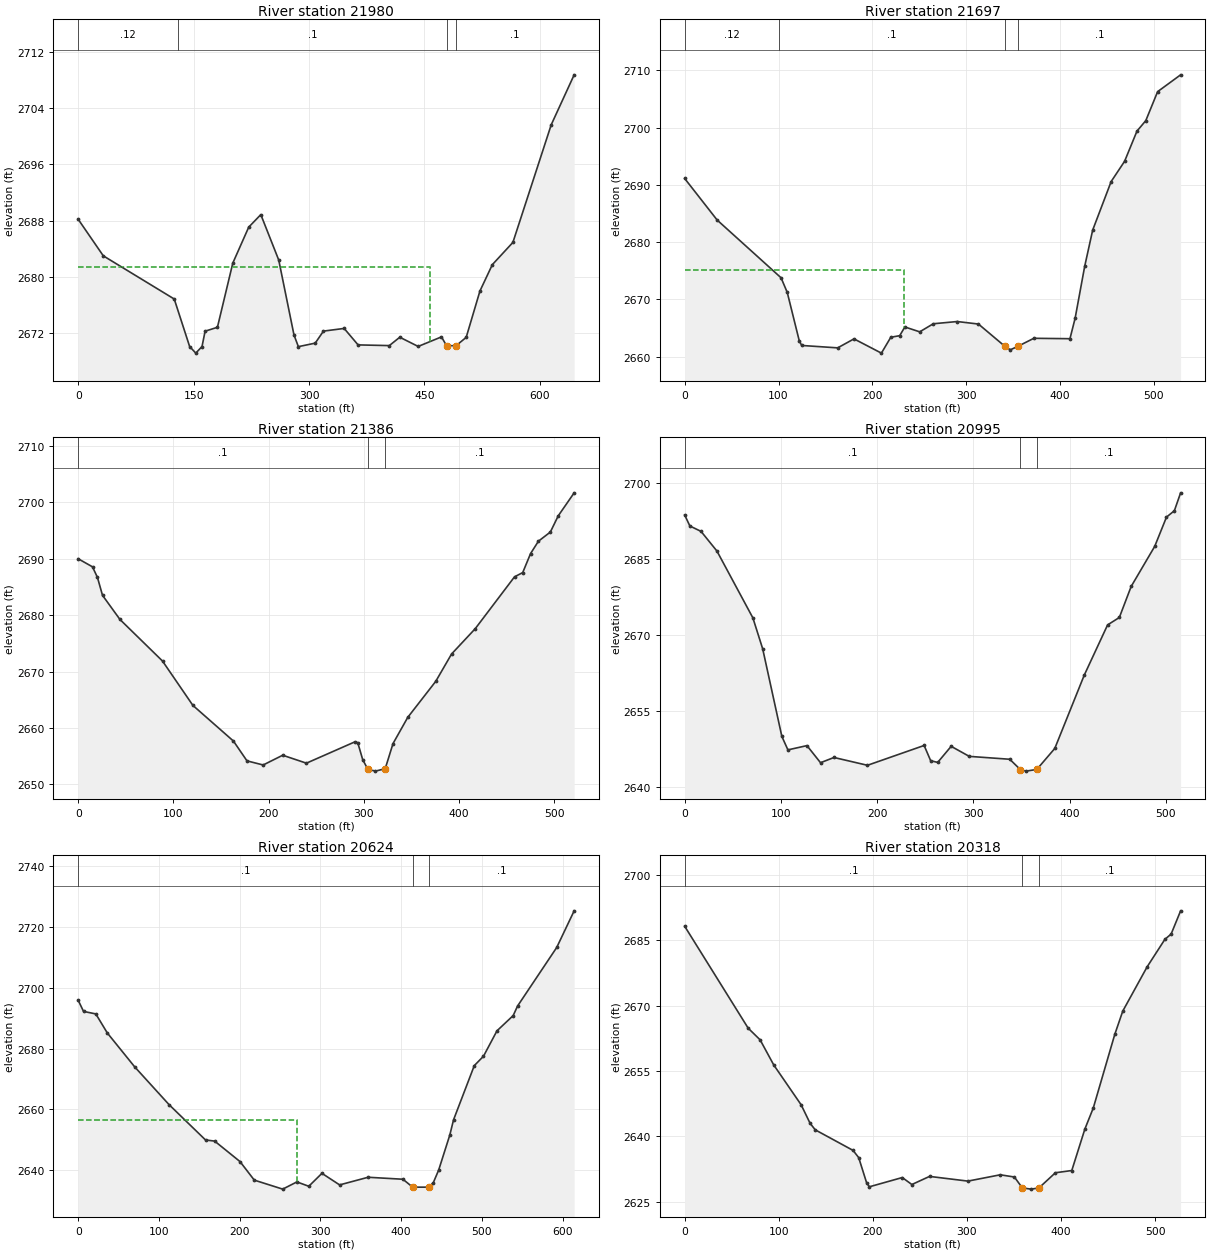
Type RM Length L Ch R = 1 ,21980   ,283.1,283.5,282.7
XS GIS Cut Line= 3
2237364.98071098620905.7370913442237350.64138754620669.790041948
2237655.67790443620398.646471373
#Sta/Elev= 30
       0 2688.17    32.6 2682.98   124.8 2676.84   144.8 2670.09   152.8 2669.15
   160.9 2670.09   164.9 2672.27   180.9 2672.82   200.9 2681.95   221.6 2687.06
   237.3 2688.84   260.6 2682.38   280.4 2671.74   286.1 2670.07     308 2670.57
   318.7 2672.28   345.6 2672.66   363.7 2670.32   404.3 2670.22   417.9 2671.41
   441.8  2670.1   472.1 2671.46   478.7  2670.2  491.112670.209   504.2 2671.39
   522.1 2677.99   538.2 2681.73   564.9 2684.89   614.7 2701.61   644.5 2708.71
#Mann= 4 ,-1,0
       0     .12       0     130      .1       0   478.7    .045       0
  491.11      .1       0
#XS Ineff= 2 , 0
          457.36 2681.35
Permanent Ineff=
       F       F
Bank Sta=478.7,491.11
XS Rating Curve= 0 ,0
Exp/Cntr(USF)=0,0
Exp/Cntr=0.3,0.1

Type RM Length L Ch R = 1 ,21697   ,310.2,311.1,309.2
XS GIS Cut Line= 2
2237461.44525051620940.9336125242237845.99983378620578.539801851
#Sta/Elev= 30
       0  2691.1    34.6 2683.84   102.7 2673.75   109.3 2671.19   122.1 2662.73
   124.7 2661.93     163 2661.51   180.4 2663.08   209.6 2660.59   219.6 2663.36
   229.1 2663.64   234.6 2665.16   250.4 2664.31   264.9 2665.72   290.4 2666.11
     313 2665.67  340.862661.822     347 2661.17   355.4 2661.81     372 2663.18
   410.5 2663.11     416 2666.68   426.2 2675.76   434.7 2682.08   454.4 2690.57
   468.7  2694.1   481.9 2699.38   491.3 2701.21   503.9 2706.27   528.4 2709.21
#Mann= 4 ,-1,0
       0     .12       0     100      .1       0  340.86    .045       0
   355.4      .1       0
#XS Ineff= 2 , 0
          233.94 2675.09
Permanent Ineff=
       F       F
Bank Sta=340.86,355.4
XS Rating Curve= 0 ,0
Exp/Cntr(USF)=0,0
Exp/Cntr=0.3,0.1

Type RM Length L Ch R = 1 ,21386   ,391.8,390.9,388.8
XS GIS Cut Line= 3
2237737.80312052621132.5591167292237963.32157105620867.933420446
 2238008.9466911620701.075838553
#Sta/Elev= 30
       0 2690.01      15 2688.58    20.2  2686.7    25.5 2683.53    43.8 2679.25
    88.5 2671.87   120.4    2664     163 2657.67   177.2 2654.16   194.2 2653.43
   214.7 2655.16   239.6 2653.75   290.7 2657.55   293.5 2657.38   298.7 2654.38
     304 2652.69     312 2652.34  322.332652.772   330.5 2657.22     346 2661.88
   375.4 2668.27     392 2673.12   416.9 2677.62   458.1 2686.81   466.7 2687.56
   474.9 2690.92   483.2 2693.13   495.7 2694.75     504 2697.63   520.7 2701.71
#Mann= 3 ,-1,0
       0      .1       0     304    .045       0  322.33      .1       0
Bank Sta=304,322.33
XS Rating Curve= 0 ,0
Exp/Cntr(USF)=0,0
Exp/Cntr=0.3,0.1

Type RM Length L Ch R = 1 ,20995   ,369.4,370.5,369.7
XS GIS Cut Line= 3
2238109.32195521621313.7560220652238316.59035771620973.522983987
2238340.05470517620858.808396436
#Sta/Elev= 30
       0 2693.61     5.4 2691.44      17 2690.38    33.5 2686.51    70.9 2673.32
    81.1 2667.21     101 2649.96   107.3  2647.3   127.1 2648.14   141.2 2644.77
   155.2  2645.8     190 2644.26   248.9 2648.17   255.7 2645.16     263 2644.83
     277    2648   295.8 2646.02   337.9 2645.45   348.9 2643.42   354.7 2643.11
     366 2643.44   384.7 2647.58   415.3 2662.02   439.6 2671.94   451.8  2673.4
   464.1 2679.52   488.6 2687.43   500.8 2693.19     509 2694.45   515.5 2697.98
#Mann= 3 ,-1,0
       0      .1       0   348.9    .045       0     366      .1       0
Bank Sta=348.9,366
XS Rating Curve= 0 ,0
Exp/Cntr(USF)=0,0
Exp/Cntr=0.3,0.1

Type RM Length L Ch R = 1 ,20624   ,300.1,305.9,309.7
XS GIS Cut Line= 4
2238383.69407203621491.5392033952238512.89841245621352.407103073
2238651.60909636621107.7911944172238746.76058618621000.808648263
#Sta/Elev= 30
       0 2695.88     6.6 2692.23    21.8 2691.41      36 2685.16    69.9 2674.02
   112.4 2661.62   157.7 2649.97     169  2649.6   200.4 2642.87   218.1 2636.77
   253.3 2633.81   270.9 2636.18   285.6 2634.75   301.9    2639   323.8  2635.2
   359.1 2637.71   402.2 2637.06   414.3 2634.46     434 2634.45   439.8  2635.9
   446.5 2640.09   460.3 2651.61   464.9 2656.59   490.6 2674.41     502  2677.5
   518.7 2685.85   538.8 2690.87   544.2    2694   592.7 2713.25   614.3  2725.3
#Mann= 3 ,-1,0
       0      .1       0   414.3    .045       0     434      .1       0
#XS Ineff= 2 , 0
           271.5 2656.59
Permanent Ineff=
       F       F
Bank Sta=414.3,434
XS Rating Curve= 0 ,0
Exp/Cntr=0.3,0.1

Type RM Length L Ch R = 1 ,20318   ,334.8,338.9,336.3
XS GIS Cut Line= 3
2238502.76178534621562.1444436642238858.06754883621342.611968572
2238944.10348949621274.826075928
#Sta/Elev= 30
       0 2688.26    67.5 2664.86    80.2 2662.18    94.7 2656.41   123.8 2647.27
   133.3 2643.03   138.8 2641.52     179  2636.8     185 2635.14   193.5  2629.3
   196.4 2628.45   231.3 2630.57   241.5 2628.97   260.3 2630.83   301.1 2629.75
   335.5  2631.2   350.5 2630.69     359 2628.17   368.4 2627.91   376.6 2628.19
   394.1 2631.67   411.5 2632.18   425.4 2641.69   434.4 2646.56   457.2 2663.43
   465.7 2668.78   491.6 2678.94   510.5 2685.26   517.1 2686.46   527.2  2691.8
#Mann= 3 ,-1,0
       0      .1       0     359    .045       0   376.6      .1       0
Bank Sta=359,376.6
XS Rating Curve= 0 ,0
Exp/Cntr(USF)=0,0
Exp/Cntr=0.3,0.1

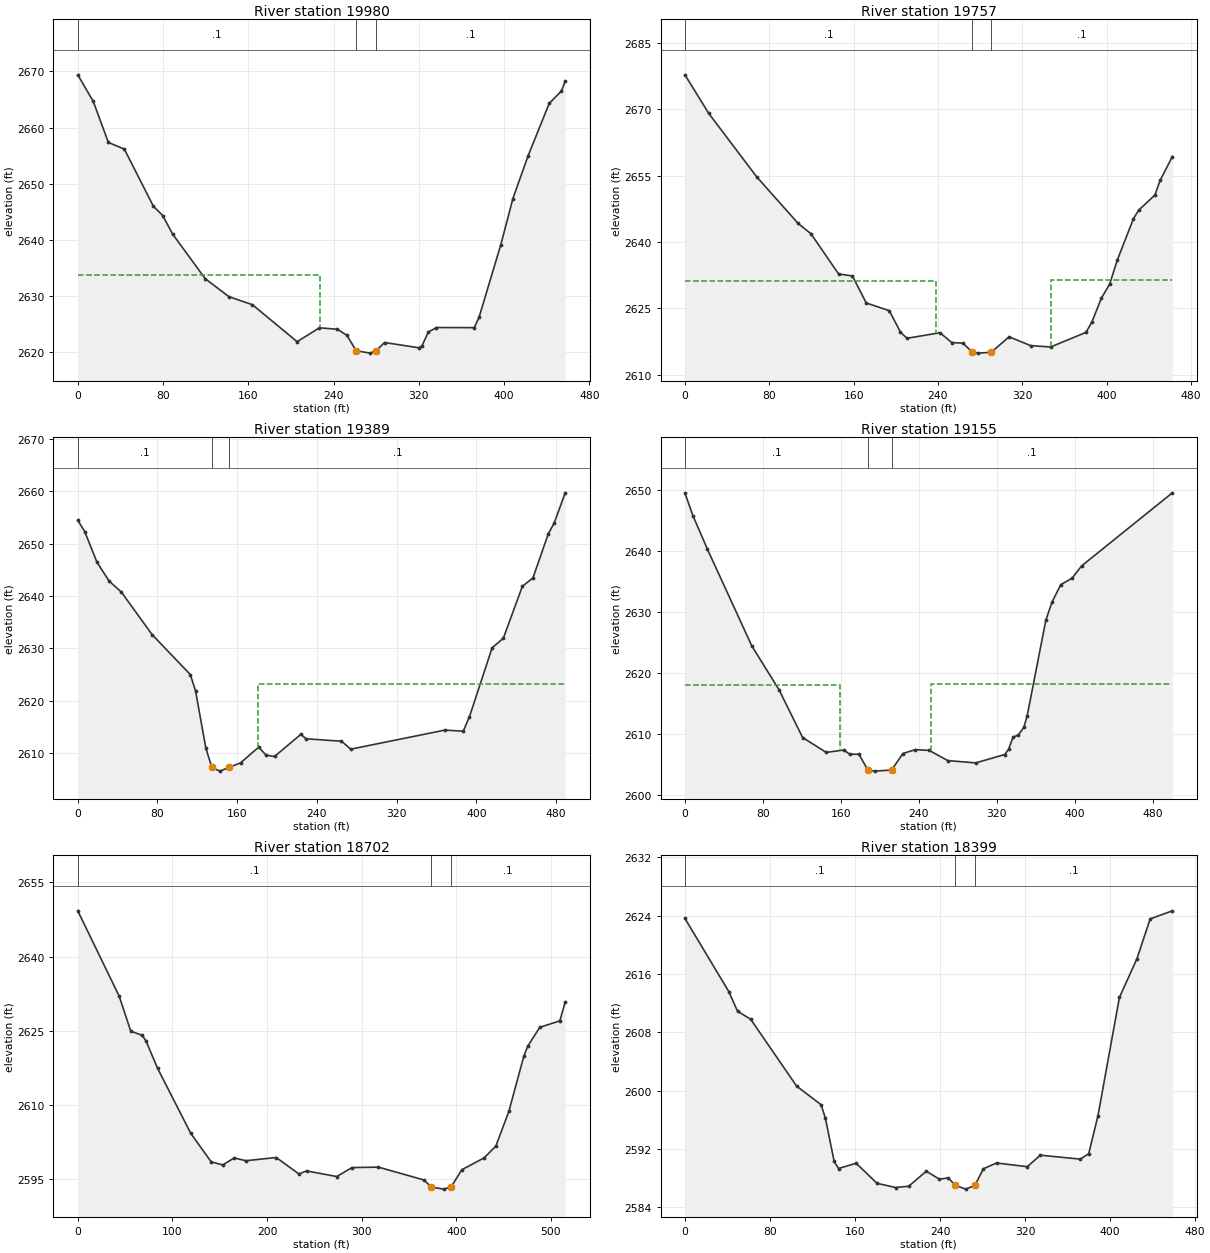
Type RM Length L Ch R = 1 ,19980   ,222.2,222.5,222.7
XS GIS Cut Line= 3
2238688.14746643621755.3898479342239030.98765423621592.442990617
2239090.95209772621542.907145992
#Sta/Elev= 30
       0  2669.4    14.5 2664.67    28.7 2657.36    43.7 2656.17    70.9 2646.01
    79.7 2644.34      89 2641.04   119.6 2633.09   141.8  2629.9   163.9 2628.46
   205.8 2621.88   226.8 2624.35   243.6 2624.09   252.5 2623.02   261.3 2620.25
   274.6 2619.84  279.932620.293   287.9 2621.73   319.9  2620.8   322.9  2621.1
   328.9 2623.58   336.6  2624.4   372.1 2624.38   376.5 2626.19     397 2639.17
   408.3 2647.36   422.6    2655   442.4 2664.32   453.8  2666.5   457.4 2668.27
#Mann= 3 ,-1,0
       0      .1       0   261.3    .045       0  279.93      .1       0
#XS Ineff= 2 , 0
          227.44 2633.69
Permanent Ineff=
       F       F
Bank Sta=261.3,279.93
XS Rating Curve= 0 ,0
Exp/Cntr(USF)=0,0
Exp/Cntr=0.3,0.1

Type RM Length L Ch R = 1 ,19757   ,370.6,368.1,365.5
XS GIS Cut Line= 3
 2238770.7280333621953.3559268132239131.81826912621794.319794071
2239185.26483832621752.605398598
#Sta/Elev= 30
       0 2677.81    22.5 2669.13      68 2654.78   107.4 2644.22   119.6 2641.88
   145.8 2632.79   158.9 2632.36     172 2626.25   193.9  2624.5   204.5 2619.65
   210.6 2618.26     242 2619.52   253.1 2617.31   263.8 2617.16   272.6 2615.13
   278.3 2614.91   290.6  2615.1   307.5  2618.6   327.9 2616.61   346.9  2616.3
   380.5  2619.6   386.2 2622.01     395 2627.31   402.9 2630.49   410.2 2635.96
   425.5  2645.3   430.5 2647.23   445.8 2650.63   450.8 2653.96   462.4 2659.34
#Mann= 3 ,-1,0
       0      .1       0   272.6    .045       0   290.6      .1       0
#XS Ineff= 2 , 0
          238.27 2631.24  346.93         2631.48
Permanent Ineff=
       F       F
Bank Sta=272.6,290.6
XS Rating Curve= 0 ,0
Exp/Cntr(USF)=0,0
Exp/Cntr=0.3,0.1

Type RM Length L Ch R = 1 ,19389   ,231.9,233.6,234.4
XS GIS Cut Line= 3
2238933.31009142622233.8254651812239044.73647186622212.259068968
2239328.69402199621966.042712202
#Sta/Elev= 30
       0  2654.5       7 2652.33    19.2 2646.51    31.4 2642.89    43.7 2640.79
    74.7 2632.63   112.9 2625.03   118.2 2621.91   128.6 2610.93  134.582607.289
   142.6 2606.57   152.1  2607.3   163.5 2608.16   181.6 2611.16     189 2609.62
   197.5 2609.37   223.9  2613.6   229.2 2612.75   264.7 2612.28   274.1 2610.77
   368.5 2614.41   386.9  2614.2   393.2 2616.98   415.9 2630.12   427.2 2631.97
   446.3 2641.89   456.9 2643.48   472.3 2651.91   478.1 2653.91   489.3 2659.74
#Mann= 3 ,-1,0
       0      .1       0  134.58    .045       0   152.1      .1       0
#XS Ineff= 2 , 0
                          180.87         2623.17
Permanent Ineff=
       F       F
Bank Sta=134.58,152.1
XS Rating Curve= 0 ,0
Exp/Cntr(USF)=0,0
Exp/Cntr=0.3,0.1

Type RM Length L Ch R = 1 ,19155   ,443.2,453.2,456.4
XS GIS Cut Line= 4
2239015.98127691622420.7342323612239159.75725166622406.356634886
2239355.65201726622276.958257607 2239467.0783977622230.231065812
#Sta/Elev= 30
       0 2649.49     8.2 2645.79      23 2640.32    68.5  2624.5    96.7 2617.23
   120.8 2609.45     145 2607.03     163 2607.41     169 2606.74   178.6 2606.72
  187.632604.146   194.7 2603.96   212.1 2604.14   223.6 2606.84   236.1 2607.47
   250.5 2607.36   269.8 2605.68   298.4 2605.31   328.1 2606.68     332 2607.52
   336.7 2609.53     342 2609.85   347.7 2611.12   351.1 2612.98   370.3 2628.67
   376.6 2631.62   385.6 2634.49   397.2 2635.54     407 2637.56   500.1 2649.52
#Mann= 3 ,-1,0
       0      .1       0  187.63    .045       0   212.1      .1       0
#XS Ineff= 2 , 0
          159.42  2618.1  252.49         2618.17
Permanent Ineff=
       F       F
Bank Sta=187.63,212.1
XS Rating Curve= 0 ,0
Exp/Cntr(USF)=0,0
Exp/Cntr=0.3,0.1

Type RM Length L Ch R = 1 ,18702   ,304,303.2,298.6
XS GIS Cut Line= 4
2239060.91126902 622753.216173982239253.21163525622722.663779345
2239503.02239138622729.8525780822239569.51877971622706.488982185
#Sta/Elev= 30
       0 2649.25    43.8 2631.94      56 2624.88    68.1 2624.05    72.2 2622.86
    84.3 2617.37   119.4  2604.2     141 2598.42   153.2 2597.81   165.3 2599.23
   177.6 2598.66   209.7 2599.31   233.7 2595.98   241.7  2596.6   273.7 2595.46
   289.7 2597.27   317.7 2597.36   365.7 2594.77   373.7 2593.32   386.7 2592.91
   394.5 2593.34   405.8 2596.83   429.5 2599.25   441.8 2601.63   455.5 2608.63
   471.3 2619.78   475.5 2621.85   488.2 2625.66   509.4 2626.98   515.1  2630.8
#Mann= 3 ,-1,0
       0      .1       0   373.7    .045       0   394.5      .1       0
Bank Sta=373.7,394.5
XS Rating Curve= 0 ,0
Exp/Cntr(USF)=0,0
Exp/Cntr=0.3,0.1

Type RM Length L Ch R = 1 ,18399   ,259.4,259.4,258
XS GIS Cut Line= 2
 2239184.1766469623085.0737363582239628.40968522622971.382218692
#Sta/Elev= 30
       0 2623.64    41.3 2613.59    49.5  2610.9    61.9 2609.79   105.1 2600.62
     128 2598.08   132.1 2596.28   140.4 2590.28   144.5 2589.31   161.1 2590.03
   180.7 2587.28   198.2  2586.7   210.6 2586.88   227.1 2588.94   239.5 2587.84
   247.7 2588.03  254.42 2587.01   264.2 2586.48   272.8 2586.99   280.8 2589.27
   293.2 2590.07   322.1 2589.56   334.4 2591.14   371.9  2590.6   379.9 2591.34
   388.6 2596.55   408.8 2612.79   425.3 2618.11   437.7 2623.57   458.6 2624.68
#Mann= 3 ,-1,0
       0      .1       0  254.42    .045       0   272.8      .1       0
Bank Sta=254.42,272.8
XS Rating Curve= 0 ,0
Exp/Cntr(USF)=0,0
Exp/Cntr=0.3,0.1

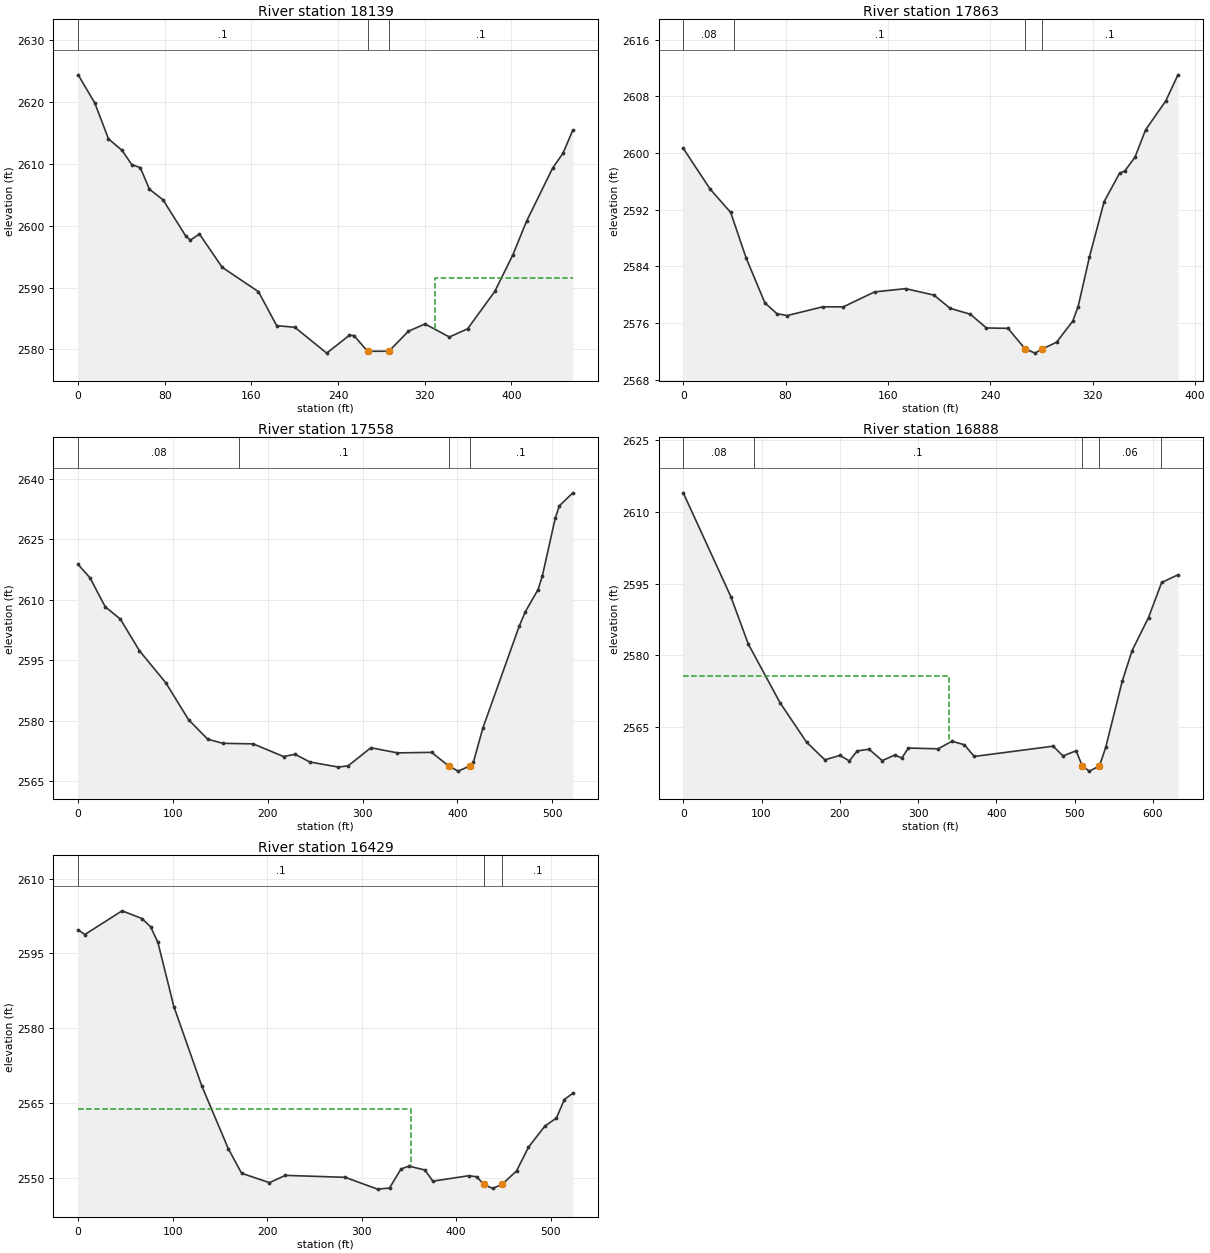
Type RM Length L Ch R = 1 ,18139   ,276.5,276.9,276.6
XS GIS Cut Line= 2
2239213.44986039623348.6363762412239648.84386314623210.457441236
#Sta/Elev= 30
       0 2624.43    15.4 2619.86      28 2614.07    40.6 2612.19    49.5  2609.9
    57.4 2609.41    65.8 2605.92    78.4  2604.2    99.4 2598.33   103.6 2597.68
     112 2598.67     133 2593.28   166.5 2589.33   183.3 2583.84   200.1 2583.57
   229.5 2579.39   250.5 2582.28   254.7 2582.24   267.2 2579.69  286.932579.699
     305 2582.94   320.3 2584.11   342.8    2582   359.6 2583.32   384.8  2589.4
   401.5 2595.33   414.1 2600.76   438.2 2609.35   447.7 2611.74   456.8 2615.49
#Mann= 3 ,-1,0
       0      .1       0   267.2    .045       0  286.93      .1       0
#XS Ineff= 2 , 0
                          329.46          2591.6
Permanent Ineff=
       F       F
Bank Sta=267.2,286.93
XS Rating Curve= 0 ,0
Exp/Cntr(USF)=0,0
Exp/Cntr=0.3,0.1

Type RM Length L Ch R = 1 ,17863   ,302.1,304.8,308.2
XS GIS Cut Line= 4
2239287.12547429623544.628154249 2239448.3565719  623549.1336738
2239594.27548262623500.8477797042239665.60806512623494.777614803
#Sta/Elev= 30
       0 2600.68    21.1  2594.9    37.1 2591.62    49.1 2585.22    63.8 2578.86
    73.1 2577.35    81.1 2577.07   109.1 2578.31   125.1  2578.3   149.5 2580.41
   173.8 2580.87   195.9 2579.96   208.6 2578.09   224.4 2577.26   236.9 2575.32
   253.8 2575.27267.01392572.395   274.9 2571.77   280.7 2572.37   291.7  2573.3
   304.4 2576.29   308.6 2578.34   317.4 2585.32   328.9 2593.15     341 2597.17
     345 2597.47     353 2599.42   361.3 2603.28   377.1 2607.37   386.6 2611.05
#Mann= 4 ,-1,0
       0     .08       0      40      .1       0267.0139    .045       0
   280.7      .1       0
Bank Sta=267.0139,280.7
XS Rating Curve= 0 ,0
Exp/Cntr(USF)=0,0
Exp/Cntr=0.3,0.1

Type RM Length L Ch R = 1 ,17558   ,670.6,669.7,663
XS GIS Cut Line= 3
2239251.66123743623820.0354920582239678.17931767623800.544074412
2239722.89492286623716.845633935
#Sta/Elev= 30
       0 2618.74    12.5 2615.44    28.5 2608.28    44.6  2605.2    64.6  2597.4
    92.6  2589.4   116.6 2580.26   136.7 2575.47   152.6 2574.45   184.7 2574.31
   216.7 2571.17   228.8 2571.74   244.5 2569.82   274.5 2568.57   284.8 2568.86
   308.8 2573.35   336.9 2572.08   372.9 2572.21   390.92568.836   400.9 2567.56
  413.03 2568.83   416.9  2569.7     427 2578.25   465.2 2603.39   471.6 2606.97
   485.2 2612.53   489.7  2615.9   503.3 2630.17   507.6 2633.26   521.9 2636.49
#Mann= 4 ,-1,0
       0     .08       0     170      .1       0   390.9    .045       0
  413.03      .1       0
Bank Sta=390.9,413.03
XS Rating Curve= 0 ,0
Exp/Cntr(USF)=0,0
Exp/Cntr=0.3,0.1

Type RM Length L Ch R = 1 ,16888   ,458.7,458.7,458.3
XS GIS Cut Line= 2
2239434.15740307624410.4663203572240036.01791526624218.293314711
#Sta/Elev= 30
       0 2613.95    60.9 2592.23    83.1 2582.37   123.6 2570.13   157.5 2561.88
   180.9  2558.2     200 2559.12   212.1 2557.98   222.2 2560.06   237.3 2560.42
   254.1 2558.03     270 2559.19   279.2  2558.6   287.6 2560.66   325.4  2560.5
   343.2 2562.07     359 2561.35   371.6  2558.9   472.4 2561.05     485 2559.02
   501.8 2560.09  509.59 2556.92   518.6 2555.84   531.6 2556.92   539.6 2560.83
   560.6 2574.59   573.2 2580.99   594.2 2587.91     611 2595.23   631.8 2596.83
#Mann= 5 ,-1,0
       0     .08       0      90      .1       0  509.59    .045       0
   531.6     .06       0     610      .1       0
#XS Ineff= 2 , 0
          339.16 2575.71
Permanent Ineff=
       F       F
Bank Sta=509.59,531.6
XS Rating Curve= 0 ,0
Exp/Cntr(USF)=0,0
Exp/Cntr=0.3,0.1

Type RM Length L Ch R = 1 ,16429   ,549.2,554.1,557.1
XS GIS Cut Line= 2
2239660.10916097624822.1336113262240156.67522821 624656.22132279
#Sta/Elev= 30
       0  2599.7     7.1 2598.79    46.5 2603.54    67.5    2602    76.7 2600.33
    84.4 2597.21   101.3 2584.34   130.8 2568.43   158.9 2555.83     173 2550.88
   202.5    2549   219.4 2550.46   282.6 2550.07   316.9  2547.7   329.6 2547.92
   341.7 2551.75   350.1 2552.31     367 2551.54   375.4  2549.3   413.4 2550.39
   421.8 2550.18   429.3 2548.67   438.7 2547.83  448.74 2548.67     464 2551.35
   476.6  2556.1   493.9 2560.33   506.2 2561.96   514.6 2565.68   523.6 2566.94
#Mann= 3 ,-1,0
       0      .1       0   429.3    .045       0  448.74      .1       0
#XS Ineff= 2 , 0
          352.42 2563.84
Permanent Ineff=
       F       F
Bank Sta=429.3,448.74
XS Rating Curve= 0 ,0
Exp/Cntr(USF)=0,0
Exp/Cntr=0.3,0.1