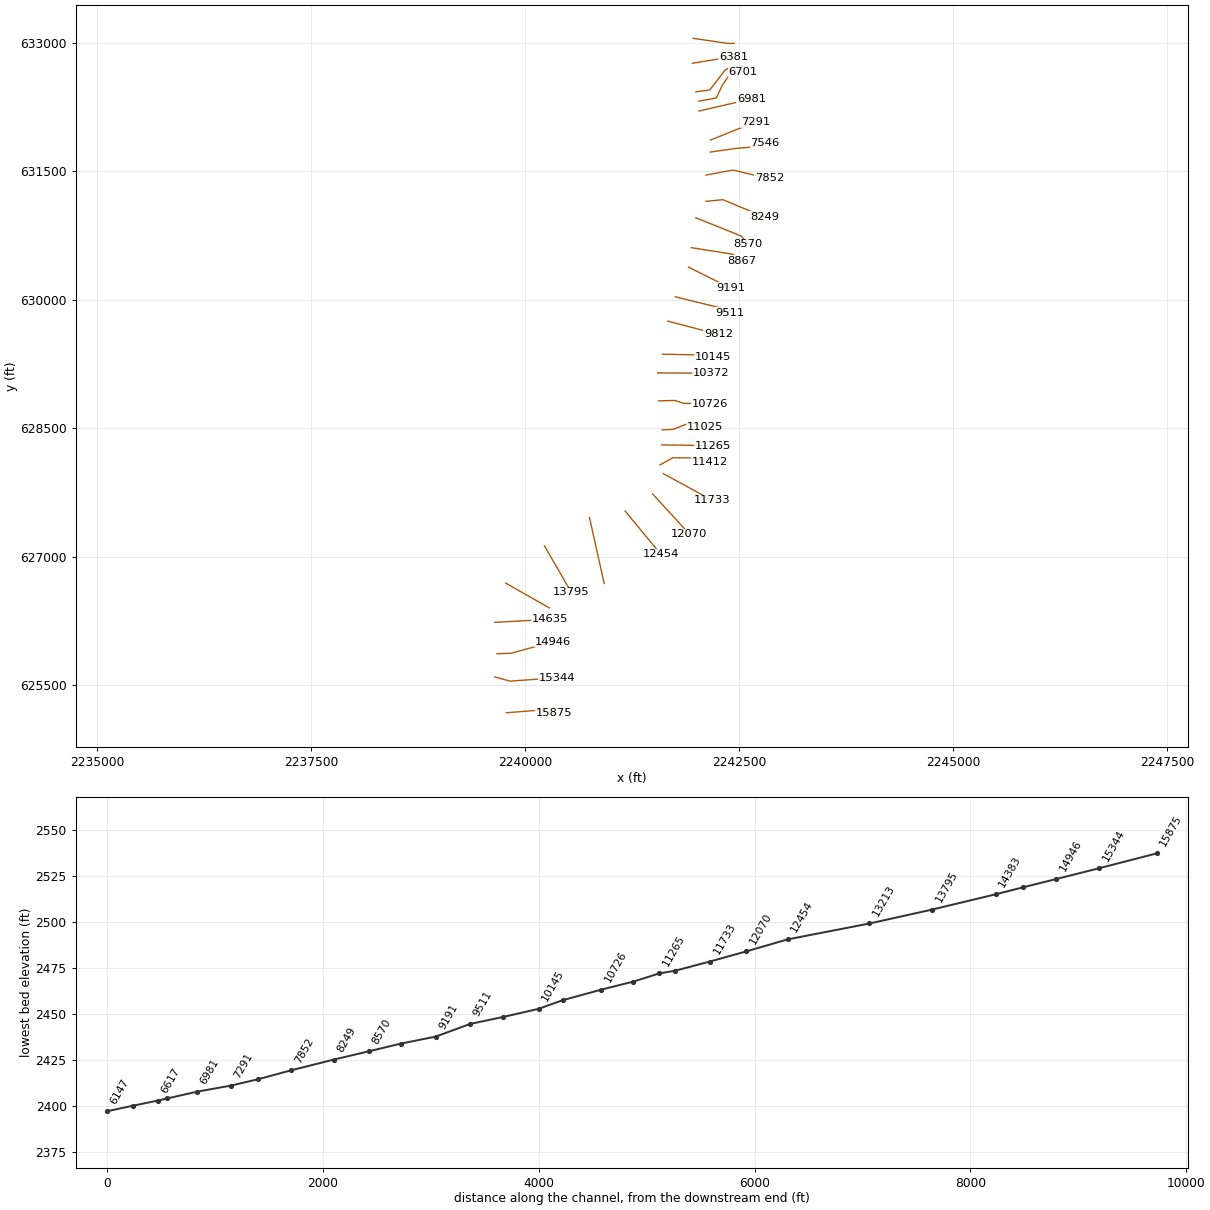
HEC-RAS study KITTLECK.prj: KITTLECK

--- KITTLECK.g01 (geometry) --- (continued)

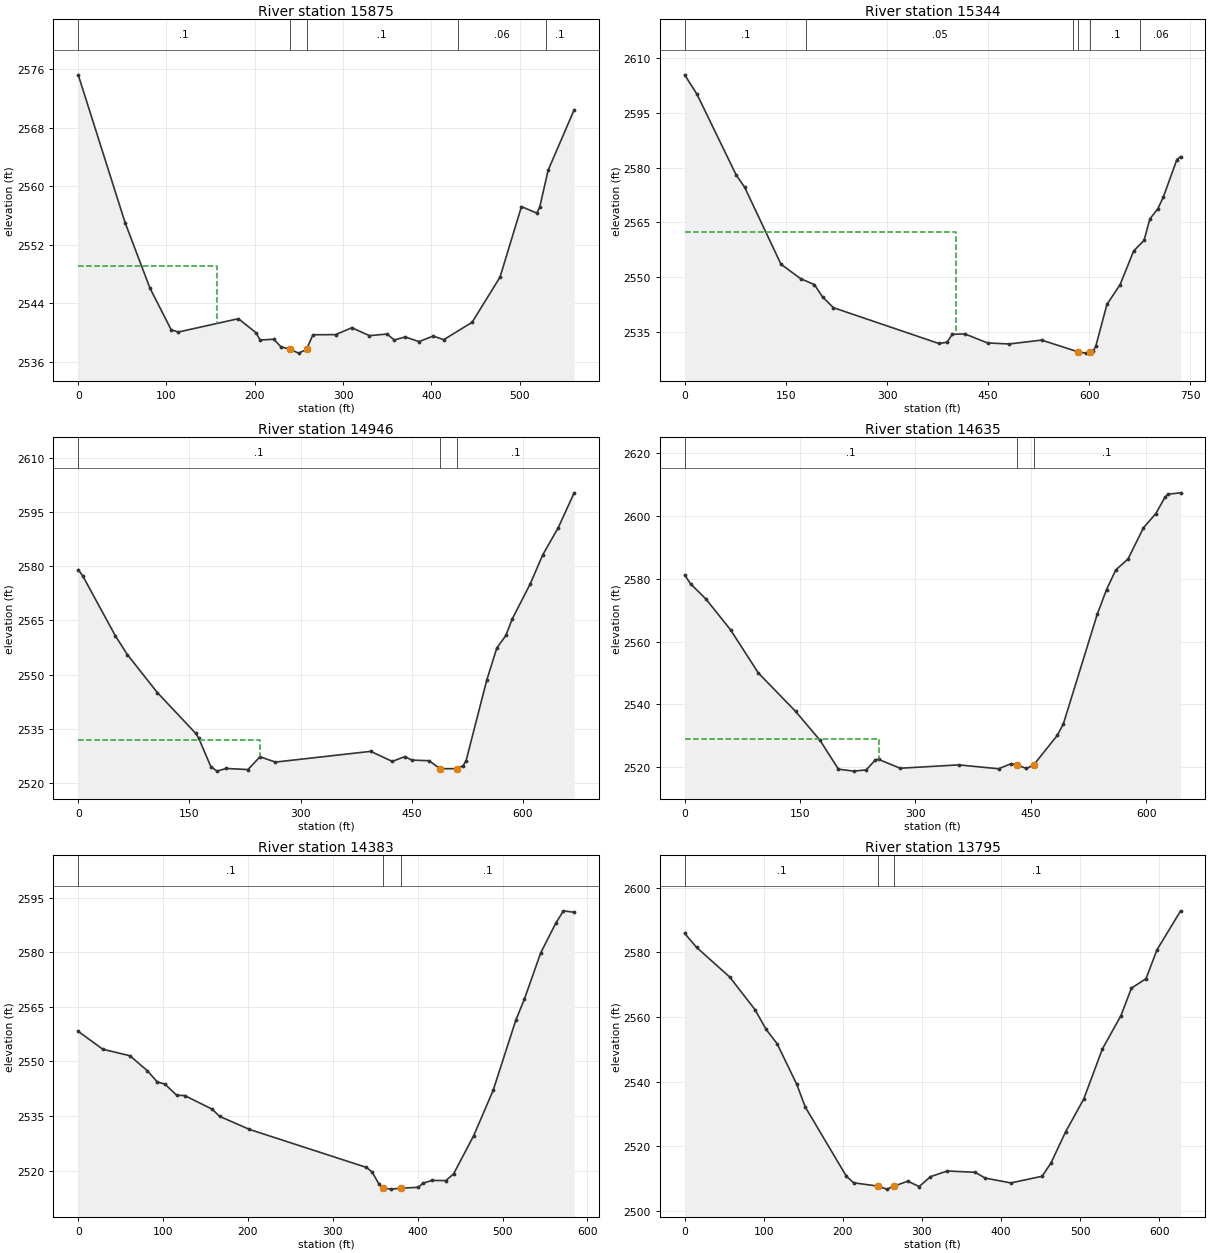
Type RM Length L Ch R = 1 ,15875   ,529,531.6,528.3
XS GIS Cut Line= 3
2239783.22772937625176.6112018232240231.98337442625211.693488838
2240335.46114669625169.457663421
#Sta/Elev= 30
       0 2575.22    53.1 2555.03    81.2 2546.09   105.3 2540.38   113.3 2540.06
   181.5 2541.89   201.6 2539.95   206.1 2538.97   221.6 2539.08   229.6 2538.05
   239.8 2537.71   249.7 2537.18  258.712537.686   265.9 2539.69   291.7 2539.71
   309.9 2540.65     330 2539.57     350 2539.79     358 2538.98   370.4 2539.39
   386.1 2538.76   402.2 2539.51   414.2 2539.02   446.3  2541.4   477.9 2547.57
   502.2 2557.21   519.5 2556.32   522.8 2557.09   532.4 2562.17   561.9 2570.44
#Mann= 5 ,-1,0
       0      .1       0   239.8    .045       0  258.71      .1       0
     430     .06       0  530.12      .1       0
#XS Ineff= 2 , 0
          156.81 2549.15
Permanent Ineff=
       F       F
Bank Sta=239.8,258.71
XS Rating Curve= 0 ,0
Exp/Cntr(USF)=0,0
Exp/Cntr=0.3,0.1

Type RM Length L Ch R = 1 ,15344   ,395.4,397.7,399.3
XS GIS Cut Line= 3
2239646.54605171625595.5553952232239825.36290474625545.884047162
2240373.73458734625585.621125611
#Sta/Elev= 30
       0 2605.42    18.3 2600.08    76.4 2577.96    88.9 2574.62   142.8 2553.52
   171.9 2549.55   192.4 2547.93   204.4 2544.56   220.5 2541.61   376.9 2531.79
   388.9 2532.13   396.9 2534.31   415.7  2534.4   449.1 2531.94   481.2 2531.66
   529.3 2532.72   583.9 2529.47   595.2 2529.15   601.5 2529.46   605.5 2529.66
   609.5 2530.97   626.1 2542.49   645.6  2547.9   665.7 2557.13   681.2 2560.05
   689.7  2565.9   701.7 2568.73   709.8 2571.96   729.8 2582.16   735.4 2583.02
#Mann= 6 ,-1,0
       0      .1       0     180     .05       0  575.59      .1       0
   583.9    .045       0   601.5      .1       0  675.59     .06       0
#XS Ineff= 2 , 0
          402.21 2562.38
Permanent Ineff=
       F       F
Bank Sta=583.9,601.5
XS Rating Curve= 0 ,0
Exp/Cntr(USF)=0,0
Exp/Cntr=0.3,0.1

Type RM Length L Ch R = 1 ,14946   ,313.2,310.9,308.8
XS GIS Cut Line= 3
2239673.88948731 625865.657865592239837.63434744625871.648531205
2240324.87515078626005.440063267
#Sta/Elev= 30
       0 2579.03     6.3 2577.21    50.3 2560.64    66.3 2555.51   106.7 2545.01
   158.4 2533.75   162.4 2532.47   178.9 2524.54   187.2 2523.27   199.7 2524.01
     229  2523.7   245.3 2527.25     266 2525.77   394.6 2528.74   423.7 2525.96
   440.5 2527.27   450.3 2526.32   473.4 2526.15   488.12523.953   510.8 2523.95
   519.1 2524.73   523.2 2526.08   551.2 2548.45   564.7  2557.3     577 2560.81
   585.4  2565.3   609.8 2575.05   626.9 2583.17   647.7 2590.63   669.1 2600.26
#Mann= 3 ,-1,0
       0      .1       0   488.1    .045       0   510.8      .1       0
#XS Ineff= 2 , 0
          245.41 2531.97
Permanent Ineff=
       F       F
Bank Sta=488.1,510.8
XS Rating Curve= 0 ,0
Exp/Cntr(USF)=0,0
Exp/Cntr=0.3,0.1

Type RM Length L Ch R = 1 ,14635   ,259.3,252.3,247.5
XS GIS Cut Line= 2
2239648.54294025626232.8036697032240292.34381883626268.045240288
#Sta/Elev= 30
       0 2581.24     7.6 2578.43    27.7 2573.56    59.7 2563.73    95.8 2549.99
   144.3 2537.74   175.9 2528.57   199.9 2519.34   219.6 2518.72     236 2519.11
     248 2522.31     252 2522.49   280.1 2519.64   356.2 2520.71   408.2 2519.47
   424.3 2521.09   432.3 2520.67   444.4 2519.57  453.732520.692   484.4  2530.1
   492.4 2533.82   536.4 2568.71   548.5 2576.59   560.5 2582.84   576.5 2586.35
   596.5 2596.29   612.5 2600.78   624.6 2606.07   628.6 2606.99   644.8 2607.41
#Mann= 3 ,-1,0
       0      .1       0   432.3    .045       0  453.73      .1       0
#XS Ineff= 2 , 0
          252.71 2528.94
Permanent Ineff=
       F       F
Bank Sta=432.3,453.73
XS Rating Curve= 0 ,0
Exp/Cntr(USF)=0,0
Exp/Cntr=0.3,0.1

Type RM Length L Ch R = 1 ,14383   ,588.7,587.7,578.3
XS GIS Cut Line= 2
 2239775.3670372626691.4797350932240283.11859517626402.282108599
#Sta/Elev= 30
       0 2558.27    28.9 2553.37    60.8 2551.58    81.5 2547.46    93.2 2544.37
   102.2 2543.78     116 2540.72   125.5 2540.64   157.7 2536.92   166.6 2534.93
   201.7 2531.35   339.6 2520.91   346.2 2519.67   354.2 2516.39   359.22515.247
   368.3 2514.95   380.6  2515.2   400.7 2515.45     406 2516.55   416.8 2517.35
     433 2517.29   442.2 2519.12   465.9 2529.61   488.9 2542.09   515.5 2561.29
   525.7 2567.15   544.9 2579.82   562.5  2587.9   571.7 2591.36   584.3 2590.96
#Mann= 3 ,-1,0
       0      .1       0   359.2    .045       0   380.6      .1       0
Bank Sta=359.2,380.6
XS Rating Curve= 0 ,0
Exp/Cntr(USF)=0,0
Exp/Cntr=0.3,0.1

Type RM Length L Ch R = 1 ,13795   ,584.4,582.1,578.3
XS GIS Cut Line= 2
2240227.92820843627126.3799825692240541.40960509626583.306577091
#Sta/Elev= 30
       0  2585.9    15.2 2581.53    56.8 2572.42    88.9 2562.28     103 2556.15
   116.9 2551.71   141.6  2539.2   152.5  2532.1   204.6 2510.59   213.8 2508.62
  244.612507.584   255.4 2506.66   264.5 2507.58   282.2 2509.12   296.5 2507.45
   310.8 2510.52     332 2512.28   367.1 2511.88   380.1 2510.08   412.4 2508.58
     452 2510.65   463.2 2514.78   481.7 2524.43   504.6 2534.57   528.1 2550.06
   551.6  2560.4   564.9 2568.93   583.3 2571.85   597.2  2580.8   627.1 2592.89
#Mann= 3 ,-1,0
       0      .1       0  244.61    .045       0   264.5      .1       0
Bank Sta=244.61,264.5
XS Rating Curve= 0 ,0
Exp/Cntr(USF)=0,0
Exp/Cntr=0.3,0.1

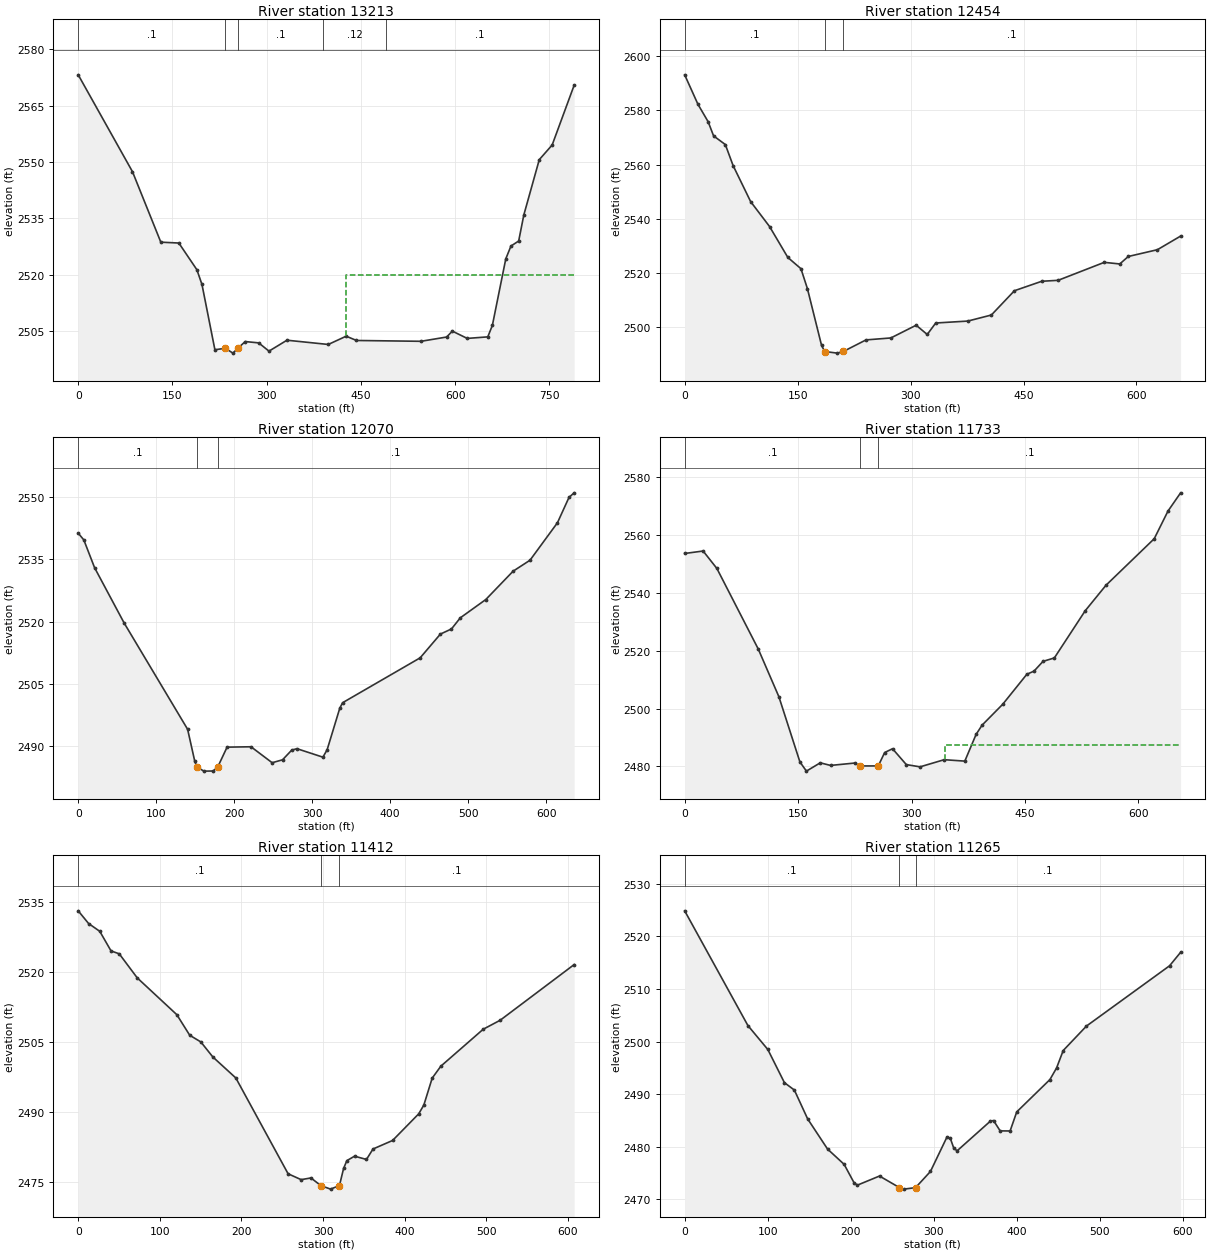
Type RM Length L Ch R = 1 ,13213   ,744.1,759.1,759.6
XS GIS Cut Line= 2
2240753.34069015627457.5223029822240925.53469677626687.064504154
#Sta/Elev= 30
       0 2573.21    86.4  2547.4   131.5 2528.63   160.2  2528.4   188.9 2521.29
     197 2517.37   217.6 2499.97   234.2 2500.36   246.3 2499.07  253.942500.343
   265.9 2502.15   287.3  2501.8   303.7  2499.6   332.3 2502.51   398.1 2501.38
   426.6 2503.58     443 2502.44   545.7 2502.22   586.5 2503.36   595.6 2504.93
   619.3 2502.99     652  2503.4   659.3 2506.45   680.7 2524.21   688.9  2527.6
   701.2 2528.94   709.4  2535.9     734 2550.62   754.5 2554.52   789.5 2570.44
#Mann= 5 ,-1,0
       0      .1       0   234.2    .045       0  253.94      .1       0
     390     .12       0     490      .1       0
#XS Ineff= 2 , 0
                           425.7         2519.79
Permanent Ineff=
       F       F
Bank Sta=234.2,253.94
XS Rating Curve= 0 ,0
Exp/Cntr(USF)=0,0
Exp/Cntr=0.3,0.1

Type RM Length L Ch R = 1 ,12454   ,383.2,384.2,384.7
XS GIS Cut Line= 2
2241168.37239841627534.788844412 2241587.8193376627027.037286445
#Sta/Elev= 30
       0 2593.14    17.7 2582.22    31.1 2575.86    38.4  2570.6      54  2567.4
    64.3 2559.65    87.6 2546.35   112.7 2537.16     137 2525.74   154.4 2521.59
     163 2514.22   181.8 2493.25  186.052491.019   202.7 2490.43   210.72491.042
   240.8 2495.31   273.8 2496.03   307.4 2500.73   322.1 2497.32   333.4 2501.55
     376 2502.26   407.3  2504.5   437.9 2513.46   474.2 2516.95   495.9  2517.3
   557.2 2523.93   577.8 2523.34   589.1  2526.1   627.8  2528.6   658.6 2533.63
#Mann= 3 ,-1,0
       0      .1       0  186.05    .045       0   210.7      .1       0
Bank Sta=186.05,210.7
XS Rating Curve= 0 ,0
Exp/Cntr(USF)=0,0
Exp/Cntr=0.3,0.1

Type RM Length L Ch R = 1 ,12070   ,332.6,336.7,340.7
XS GIS Cut Line= 2
 2241491.3448138 627732.671261992241920.67584952627263.402455501
#Sta/Elev= 30
       0 2541.33     7.2  2539.7      21 2532.99    58.9 2519.64   140.3 2493.98
   149.4 2486.32  152.15 2484.88   161.2 2483.88   173.1 2483.91     179 2484.91
   190.9 2489.67   221.6 2489.76   248.7 2485.91     262 2486.61   273.8 2488.95
   280.5  2489.3   313.8 2487.25   319.2 2489.03   335.4 2499.05     339 2500.39
   438.5 2511.23   464.5 2516.97   478.7 2518.21     490 2520.89   522.7 2525.31
   557.7 2532.15   579.4  2534.8   614.6 2543.85   629.4 2549.97     636 2551.07
#Mann= 3 ,-1,0
       0      .1       0  152.15    .045       0     179      .1       0
Bank Sta=152.15,179
XS Rating Curve= 0 ,0
Exp/Cntr(USF)=0,0
Exp/Cntr=0.3,0.1

Type RM Length L Ch R = 1 ,11733   ,314.1,320.6,325.2
XS GIS Cut Line= 2
 2241614.7165279627970.4769023632242190.90416541627656.995505706
#Sta/Elev= 30
       0  2553.6    24.4 2554.45    42.6 2548.42    97.3 2520.58   124.6 2504.09
   152.4 2481.56     161 2478.38   179.3 2481.25   192.9 2480.35   224.8 2481.17
   232.1 2480.17  256.03 2480.18   264.5 2484.81   274.9 2486.12   293.1 2480.64
   311.3 2479.86   343.2 2482.33   370.5 2481.84   385.4 2491.07   393.3 2494.26
   420.6 2501.48   452.5 2511.84   462.1 2512.96   473.9 2516.31   488.9  2517.5
   529.7  2533.8   557.2 2542.62     621  2558.7   639.2 2568.26   655.9 2574.56
#Mann= 3 ,-1,0
       0      .1       0   232.1    .045       0  256.03      .1       0
#XS Ineff= 2 , 0
                          343.99         2487.24
Permanent Ineff=
       F       F
Bank Sta=232.1,256.03
XS Rating Curve= 0 ,0
Exp/Cntr(USF)=0,0
Exp/Cntr=0.3,0.1

Type RM Length L Ch R = 1 ,11412   ,147.4,147.3,147.2
XS GIS Cut Line= 4
2241577.14626181628071.6834156752241727.02545071628155.996741648
2241975.92809859628153.8691920432242155.16625182628102.073456558
#Sta/Elev= 30
       0 2533.06    12.7 2530.34    26.4 2528.67    40.2 2524.47    50.3 2523.84
    72.3 2518.69   120.8  2510.8   136.6 2506.39   150.2 2504.96   164.9 2501.74
   193.1 2497.23   257.1  2476.7   273.1 2475.44   285.1 2475.81   297.1 2474.18
   309.1 2473.41  320.01 2474.18   325.1 2477.86   329.1 2479.52   338.5 2480.47
   353.1 2479.77   361.1 2482.01   385.1 2483.84   417.1 2489.55   423.4 2491.44
   433.6  2497.2   444.2 2499.76   496.1 2507.68   516.9 2509.61   607.5 2521.54
#Mann= 3 ,-1,0
       0      .1       0   297.1    .045       0  320.01      .1       0
Bank Sta=297.1,320.01
XS Rating Curve= 0 ,0
Exp/Cntr(USF)=0,0
Exp/Cntr=0.3,0.1

Type RM Length L Ch R = 1 ,11265   ,236.3,239.9,242.7
XS GIS Cut Line= 3
2241596.01761868628305.9892048072242055.20163631628299.366358398
2242193.43850317628291.158042698
#Sta/Elev= 30
       0 2524.87    76.2 2503.05   100.2  2498.5   120.2 2492.19   132.2 2490.78
   148.2  2485.3   172.2 2479.56   192.2 2476.65   204.2 2473.13   208.2  2472.7
   234.8 2474.43   258.72472.242   264.2 2471.94  278.262472.223   296.2  2475.3
   316.2 2481.88   320.2 2481.58   324.2 2479.78   328.3 2479.22   368.2 2484.84
   372.2 2484.99   380.2 2483.02   392.2    2483   400.2 2486.63   440.2 2492.78
   448.2 2494.98   456.2  2498.3   484.2 2502.95   584.4 2514.42   597.7 2516.98
#Mann= 3 ,-1,0
       0      .1       0   258.7    .045       0  278.26      .1       0
Bank Sta=258.7,278.26
XS Rating Curve= 0 ,0
Exp/Cntr(USF)=0,0
Exp/Cntr=0.3,0.1

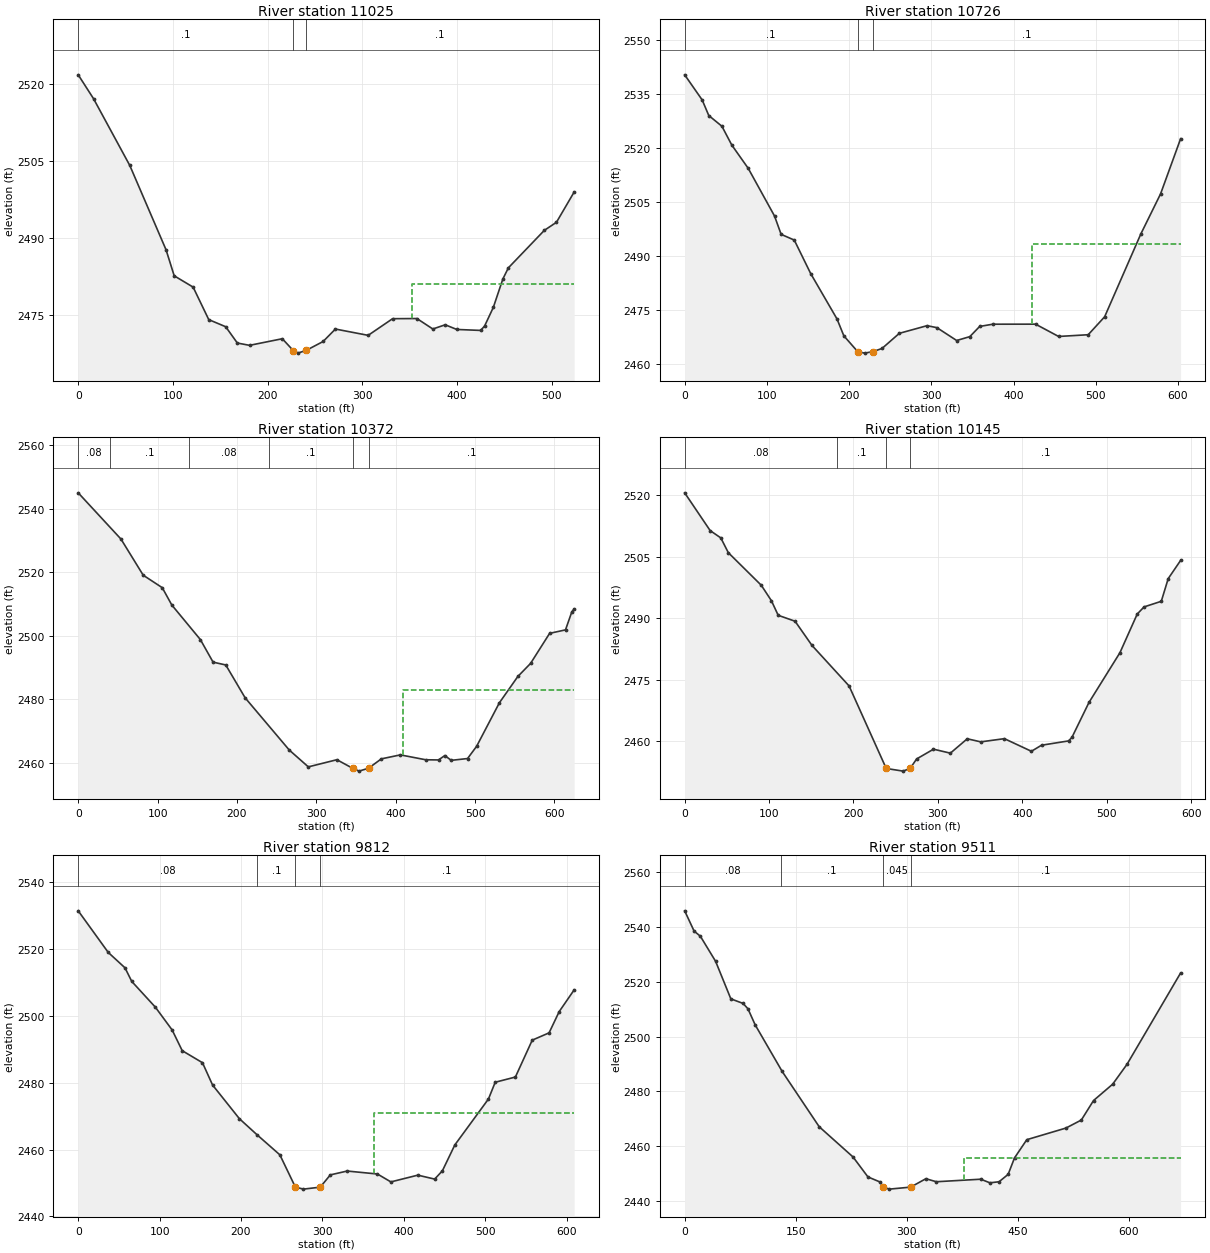
Type RM Length L Ch R = 1 ,11025   ,306.4,299.6,294.5
XS GIS Cut Line= 4
2241602.88381525628481.5818506962241734.67845878 628487.57251631
2241936.36420114628569.4449463782242102.10594982628515.528955846
#Sta/Elev= 30
       0 2521.81    16.2 2517.15    54.5 2504.12    92.8 2487.66   101.4 2482.59
   121.4 2480.38   137.9 2474.04   155.8 2472.65   168.1 2469.47     181 2469.02
   215.6 2470.31  227.19    2468   231.9  2467.5   240.7 2468.02   258.7 2469.77
   271.7  2472.2   306.3 2470.97   332.1 2474.22   357.8 2474.25   374.6 2472.21
   387.7 2473.03   399.9 2472.12   425.1 2471.93   429.3 2472.79   438.5 2476.42
   448.6 2481.97   454.4 2484.14   492.4 2491.46   505.2 2493.03   523.9 2498.94
#Mann= 3 ,-1,0
       0      .1       0  227.19    .045       0   240.7      .1       0
#XS Ineff= 2 , 0
                          352.42         2480.99
Permanent Ineff=
       F       F
Bank Sta=227.19,240.7
XS Rating Curve= 0 ,0
Exp/Cntr(USF)=0,0
Exp/Cntr=0.3,0.1

Type RM Length L Ch R = 1 ,10726   ,350.5,353.6,357
XS GIS Cut Line= 4
2241562.91110326628820.1327528112241750.99141104628825.103479659
 2241851.4369014628791.6216495392242160.53577072628787.561574107
#Sta/Elev= 30
       0 2540.23    21.3 2533.26    29.3 2528.95    45.3 2525.97    57.3 2520.76
    77.3  2514.3   109.3 2501.08   117.3 2496.01   133.3 2494.42   153.3 2485.12
   185.3 2472.54   193.6 2467.87   210.5 2463.48   218.9 2463.08  228.972463.497
     240 2464.37   261.1 2468.57   294.8 2470.69   306.8 2470.14   330.8 2466.58
   346.8 2467.65   358.8 2470.48   374.8  2471.1   426.8 2471.11   454.8  2467.7
   490.8 2468.18   510.8 2473.16   554.8 2496.11   578.8 2507.22   603.2 2522.52
#Mann= 3 ,-1,0
       0      .1       0   210.5    .045       0  228.97      .1       0
#XS Ineff= 2 , 0
                          422.53         2493.28
Permanent Ineff=
       F       F
Bank Sta=210.5,228.97
XS Rating Curve= 0 ,0
Exp/Cntr(USF)=0,0
Exp/Cntr=0.3,0.1

Type RM Length L Ch R = 1 ,10372   ,227.7,227,224.5
XS GIS Cut Line= 2
2241550.28987462629146.3481370892242175.04505246 629144.14052162
#Sta/Elev= 30
       0 2544.97    53.9 2530.41    81.9 2519.05   105.9 2515.12   117.9 2509.68
   153.9  2498.8   169.9  2491.7   185.9 2490.81   210.3 2480.47   265.9 2464.04
   289.9 2458.75   325.9    2461   345.8  2458.3   353.8 2457.41   365.8 2458.33
   381.9 2461.27   405.9 2462.52   437.9 2460.98   453.9 2460.93   461.9 2462.31
   469.9  2460.8   490.5 2461.37   501.9 2465.21   530.6 2478.91   553.9  2487.2
   569.9  2491.3   593.9 2500.76   613.9 2501.85   621.9 2507.55   624.8 2508.42
#Mann= 6 ,-1,0
       0     .08       0      40      .1       0     140     .08       0
     240      .1       0   345.8    .045       0   365.8      .1       0
#XS Ineff= 2 , 0
                          409.39         2483.03
Permanent Ineff=
       F       F
Bank Sta=345.8,365.8
XS Rating Curve= 0 ,0
Exp/Cntr(USF)=0,0
Exp/Cntr=0.3,0.1

Type RM Length L Ch R = 1 ,10145   ,335.4,332.8,328.7
XS GIS Cut Line= 3
 2241605.4182366629365.1799568262242077.07532178629356.445566359
2242190.62239785629333.153858449
#Sta/Elev= 30
       0 2520.65    30.2 2511.42    42.8 2509.64    51.7 2506.03    90.8 2498.06
   102.8 2494.28   110.8 2490.73   130.8 2489.28   150.8 2483.38   194.8 2473.47
   238.8 2453.31   258.8 2452.66  267.132453.325   274.8 2455.63   294.8 2458.02
   314.8 2457.05   334.8 2460.56   350.8 2459.81   378.8 2460.59   410.8 2457.51
   422.8 2458.99   454.8 2460.04   458.8 2460.89     479 2469.43   515.7 2481.59
   536.2 2491.04   544.3 2492.78   564.7 2494.15   572.9 2499.69   587.6 2504.14
#Mann= 4 ,-1,0
       0     .08       0     180      .1       0   238.8    .045       0
  267.13      .1       0
Bank Sta=238.8,267.13
XS Rating Curve= 0 ,0
Exp/Cntr(USF)=0,0
Exp/Cntr=0.3,0.1

Type RM Length L Ch R = 1 ,9812    ,301.4,301.4,302.4
XS GIS Cut Line= 2
2241668.50904771629751.8258647522242257.94237805629597.292781893
#Sta/Elev= 30
       0  2531.4    36.9 2518.96    57.5 2514.35    65.8 2510.29    94.8 2502.59
   115.4 2495.78   127.8 2489.58   152.7 2485.98   165.1 2479.31   198.1 2469.23
     220 2464.38   247.8 2458.43  266.792448.805   276.7 2448.18   297.4 2448.77
   309.8 2452.44   330.5 2453.59   367.7  2452.7   384.2 2450.34   417.3 2452.36
     438 2451.18   447.5 2453.66   462.8  2461.4   504.1 2475.13   512.4 2480.14
   537.2  2481.7   557.9 2492.73   578.6 2494.91     591 2501.26   609.4 2507.76
#Mann= 4 ,-1,0
       0     .08       0     220      .1       0  266.79    .045       0
   297.4      .1       0
#XS Ineff= 2 , 0
                           363.9         2470.86
Permanent Ineff=
       F       F
Bank Sta=266.79,297.4
XS Rating Curve= 0 ,0
Exp/Cntr(USF)=0,0
Exp/Cntr=0.3,0.1

Type RM Length L Ch R = 1 ,9511    ,322,319.2,314.5
XS GIS Cut Line= 3
2241755.59811327630036.0171712662242294.25628781629903.560243101
 2242395.8065994629848.369856365
#Sta/Elev= 30
       0 2545.76    12.7  2538.4    21.2 2536.51    41.8 2527.38    62.4 2513.71
    78.9 2512.06    85.5 2510.11    95.3 2504.24   131.8 2487.28   181.8 2467.17
   227.6 2456.14   247.7 2448.89   264.2 2447.03   268.3 2445.24   276.6 2444.45
   305.4 2445.18     326 2448.24   340.1 2447.14   400.2 2448.06   412.5 2446.75
   424.9 2447.13   437.2 2449.83   445.8 2455.82   462.4 2462.45   515.3 2466.68
   536.1  2469.6   552.6  2476.7   578.5 2482.66   597.9 2489.91   670.3 2523.14
#Mann= 4 ,-1,0
       0     .08       0     130      .1       0   268.3    .045       0
   305.4      .1       0
#XS Ineff= 2 , 0
                          378.09         2455.65
Permanent Ineff=
       F       F
Bank Sta=268.3,305.4
XS Rating Curve= 0 ,0
Exp/Cntr(USF)=0,0
Exp/Cntr=0.3,0.1

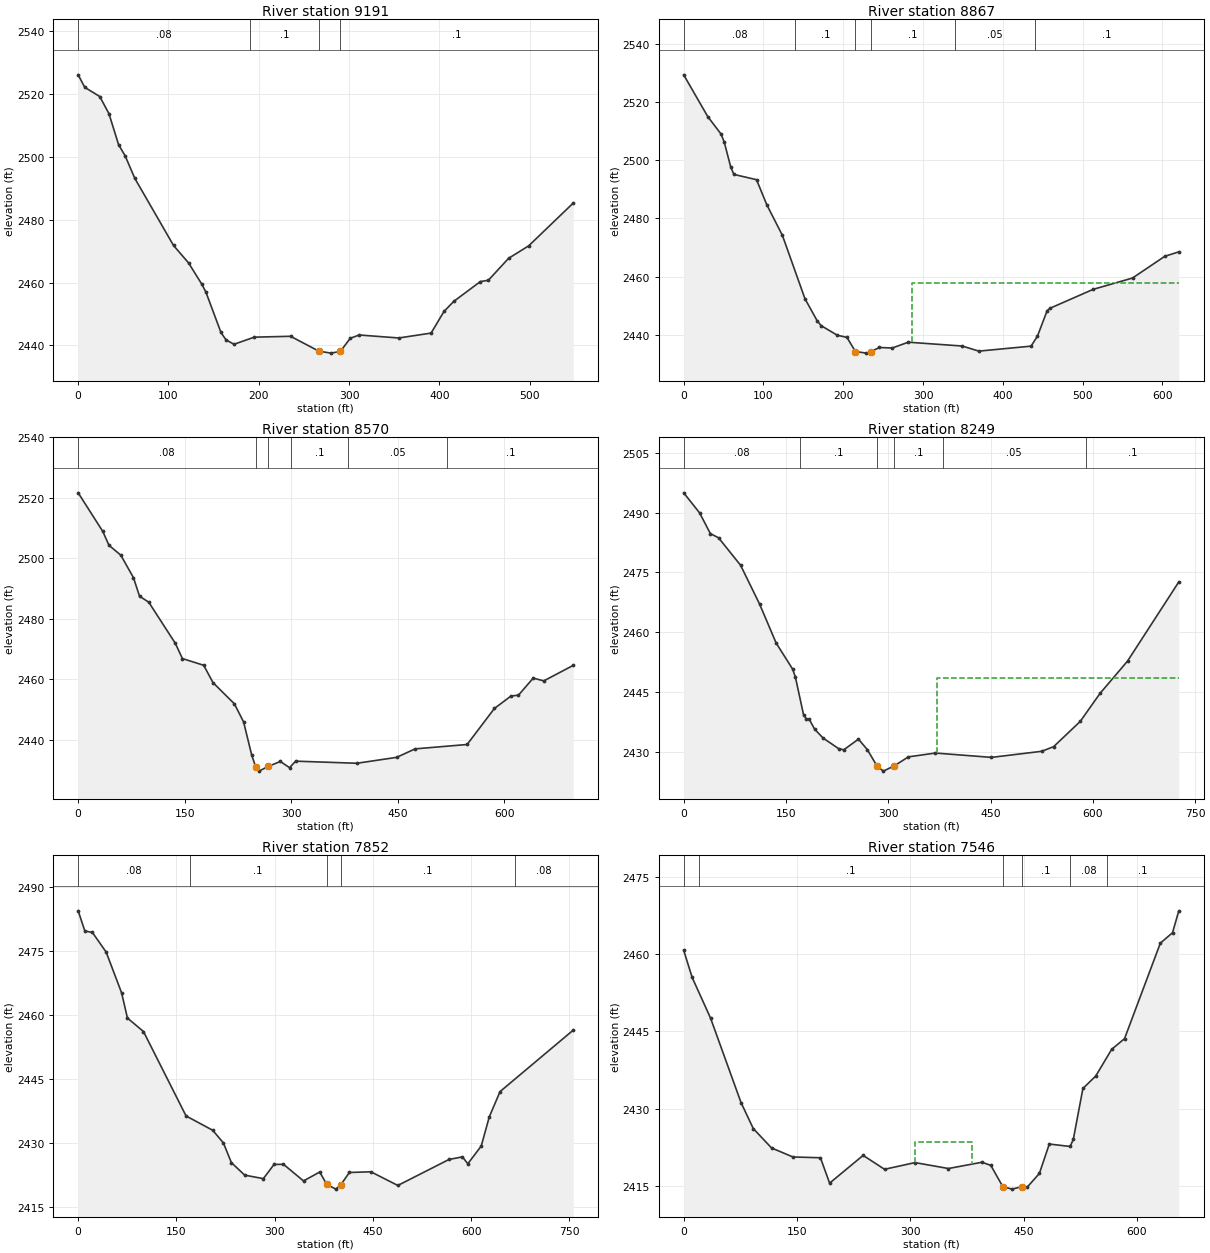
Type RM Length L Ch R = 1 ,9191    ,320.3,324.8,328.5
XS GIS Cut Line= 2
2241909.66617118630382.7364461492242400.24776904630138.173513093
#Sta/Elev= 30
       0 2526.12     7.3 2522.14    23.9 2519.22    34.1 2513.75    44.8 2503.85
      52 2500.36    62.7 2493.19   105.6 2471.82   122.3 2466.25   136.9  2459.5
   141.4 2457.02   158.1 2444.15   163.7 2441.78   172.6 2440.39     195 2442.65
   235.2 2442.93   266.5  2438.2   279.9 2437.57   290.4 2438.13   301.3  2442.3
   311.2 2443.34     355 2442.39   390.8 2443.95   405.1 2450.85   415.9 2454.04
   445.3 2460.33   454.2 2460.76   476.6 2467.74   498.9 2471.72   548.2 2485.33
#Mann= 4 ,-1,0
       0     .08       0     190      .1       0   266.5    .045       0
   290.4      .1       0
Bank Sta=266.5,290.4
XS Rating Curve= 0 ,0
Exp/Cntr(USF)=0,0
Exp/Cntr=0.3,0.1

Type RM Length L Ch R = 1 ,8867    ,298.8,296.6,294.7
XS GIS Cut Line= 3
2241942.01318739630610.2833805572242423.51353825630534.184356638
2242530.27900021630454.518056916
#Sta/Elev= 30
       0  2529.3    30.1 2514.98    46.7 2509.01    50.8 2506.25    58.8  2497.8
    62.9  2495.1    91.3 2493.29   104.3  2484.6   123.7  2474.2     152 2452.42
   167.2 2444.89   172.3 2443.17   192.5 2439.89   204.7 2439.12  215.282434.287
     229 2433.73  234.192434.177   245.2 2435.67   261.4 2435.49   281.6 2437.48
   349.1 2436.17     370 2434.42   435.5 2436.13   443.5 2439.56   455.7 2448.34
   459.8  2449.2   513.3 2455.63   562.7 2459.52   603.1 2466.97   620.7 2468.51
#Mann= 6 ,-1,0
       0     .08       0     140      .1       0  215.28    .045       0
  234.19      .1       0     340     .05       0     440      .1       0
#XS Ineff= 2 , 0
                          286.06         2457.86
Permanent Ineff=
       F       F
Bank Sta=215.28,234.19
XS Rating Curve= 0 ,0
Exp/Cntr(USF)=0,0
Exp/Cntr=0.3,0.1

Type RM Length L Ch R = 1 ,8570    ,319.4,320.8,320.7
XS GIS Cut Line= 3
2241995.98802091630959.0239284462242528.02334904630744.885227912
2242607.49750594630649.957762727
#Sta/Elev= 30
       0 2521.62    34.7 2508.84    43.3 2504.29      60    2501    77.8  2493.6
    86.4 2487.43    99.4 2485.44   136.8 2471.85   146.8 2466.79   176.8 2464.57
   189.9 2458.83   220.1  2451.8     233 2445.81   244.4 2434.88  249.992430.949
   254.6 2429.55   267.5 2431.09   284.8 2432.75   297.7 2430.68   306.3 2432.85
   392.6 2432.15   448.6 2434.11   474.5 2436.91   547.8 2438.36   586.2 2450.27
   609.6  2454.4   620.1 2454.67   640.9 2460.32   655.8 2459.41   697.3 2464.54
#Mann= 6 ,-1,0
       0     .08       0  249.99    .045       0   267.5     .08       0
     300      .1       0     380     .05       0     520      .1       0
Bank Sta=249.99,267.5
XS Rating Curve= 0 ,0
Exp/Cntr(USF)=0,0
Exp/Cntr=0.3,0.1

Type RM Length L Ch R = 1 ,8249    ,393.4,396.8,397.4
XS GIS Cut Line= 3
2242113.23181932631150.8629833242242311.91721157631170.731522549
2242797.59261484630967.630899362
#Sta/Elev= 30
       0 2494.98    23.3 2489.95    39.1 2484.75    51.2 2483.68    83.4  2476.8
   111.5 2466.97   135.6 2457.26   159.7 2450.74   163.8 2448.73   175.8 2439.24
   179.8 2438.22   183.9 2438.19   191.9 2435.68   204.3 2433.43   227.1 2430.77
   234.7 2430.46   256.3 2433.14   269.3  2430.5   283.6 2426.38   292.8 2425.11
     309 2426.45   329.5 2428.69   369.2 2429.65   451.4 2428.56   525.1 2430.09
   542.5 2431.25   581.5 2437.58   610.7 2444.65   650.9 2452.73   726.1 2472.61
#Mann= 6 ,-1,0
       0     .08       0     170      .1       0   283.6    .045       0
     309      .1       0  379.68     .05       0  589.68      .1       0
#XS Ineff= 2 , 0
                          371.41         2448.55
Permanent Ineff=
       F       F
Bank Sta=283.6,309
XS Rating Curve= 0 ,0
Exp/Cntr(USF)=0,0
Exp/Cntr=0.3,0.1

Type RM Length L Ch R = 1 ,7852    ,296.7,306.3,305.9
XS GIS Cut Line= 4
2242114.19144408631457.8880141842242431.30477291631516.709252042
2242639.35168892631466.3528046862242853.38344524631418.728717091
#Sta/Elev= 30
       0 2484.47    10.2 2479.74    21.7 2479.41    42.7 2474.81    66.3 2465.25
    75.2 2459.35    99.7 2456.19   164.7 2436.41   205.4 2433.05   221.7 2430.09
   233.9 2425.47   254.2 2422.54   282.7 2421.72     299 2425.04   313.4 2425.08
     344 2421.18   368.7 2423.27   379.52420.377   393.4 2419.26  401.25 2420.34
     414 2423.16   446.9 2423.32     488 2420.12   566.1 2426.21   586.6 2426.82
   594.8  2425.2   615.3 2429.35   627.6 2436.19     644 2442.11   755.8 2456.52
#Mann= 5 ,-1,0
       0     .08       0     170      .1       0   379.5    .045       0
  401.25      .1       0  666.58     .08       0
Bank Sta=379.5,401.25
XS Rating Curve= 0 ,0
Exp/Cntr(USF)=0,0
Exp/Cntr=0.3,0.1

Type RM Length L Ch R = 1 ,7546    ,253.4,255.2,257
XS GIS Cut Line= 4
2242161.06606809631726.2668640422242461.18742112631769.558971805
2242658.10378626631785.4393238332242803.92724701631836.407983921
#Sta/Elev= 30
       0 2460.75    11.2 2455.48    35.5 2447.61    75.9 2431.19    92.1 2426.15
   116.3 2422.39   144.6 2420.64     181 2420.49   193.1 2415.56   237.5 2420.95
   265.8 2418.25   306.2 2419.55   350.4  2418.4   394.8 2419.62   406.5 2419.01
  422.31 2414.89   434.6  2414.4   447.8 2414.88   454.7 2414.79   470.8 2417.45
   483.9 2423.15   511.5 2422.68   515.7 2424.07   528.4 2433.94   545.4 2436.36
   566.5 2441.54   583.5 2443.61   630.9 2462.15     647 2464.17   655.3 2468.42
#Mann= 6 ,-1,0
       0     .08       0      20      .1       0  422.31    .045       0
   447.8      .1       0  510.78     .08       0  560.78      .1       0
#XS Ineff= 1 ,-1
  306.64  381.41 2423.57
Permanent Ineff=
       F
Bank Sta=422.31,447.8
XS Rating Curve= 0 ,0
Exp/Cntr(USF)=0,0
Exp/Cntr=0.3,0.1

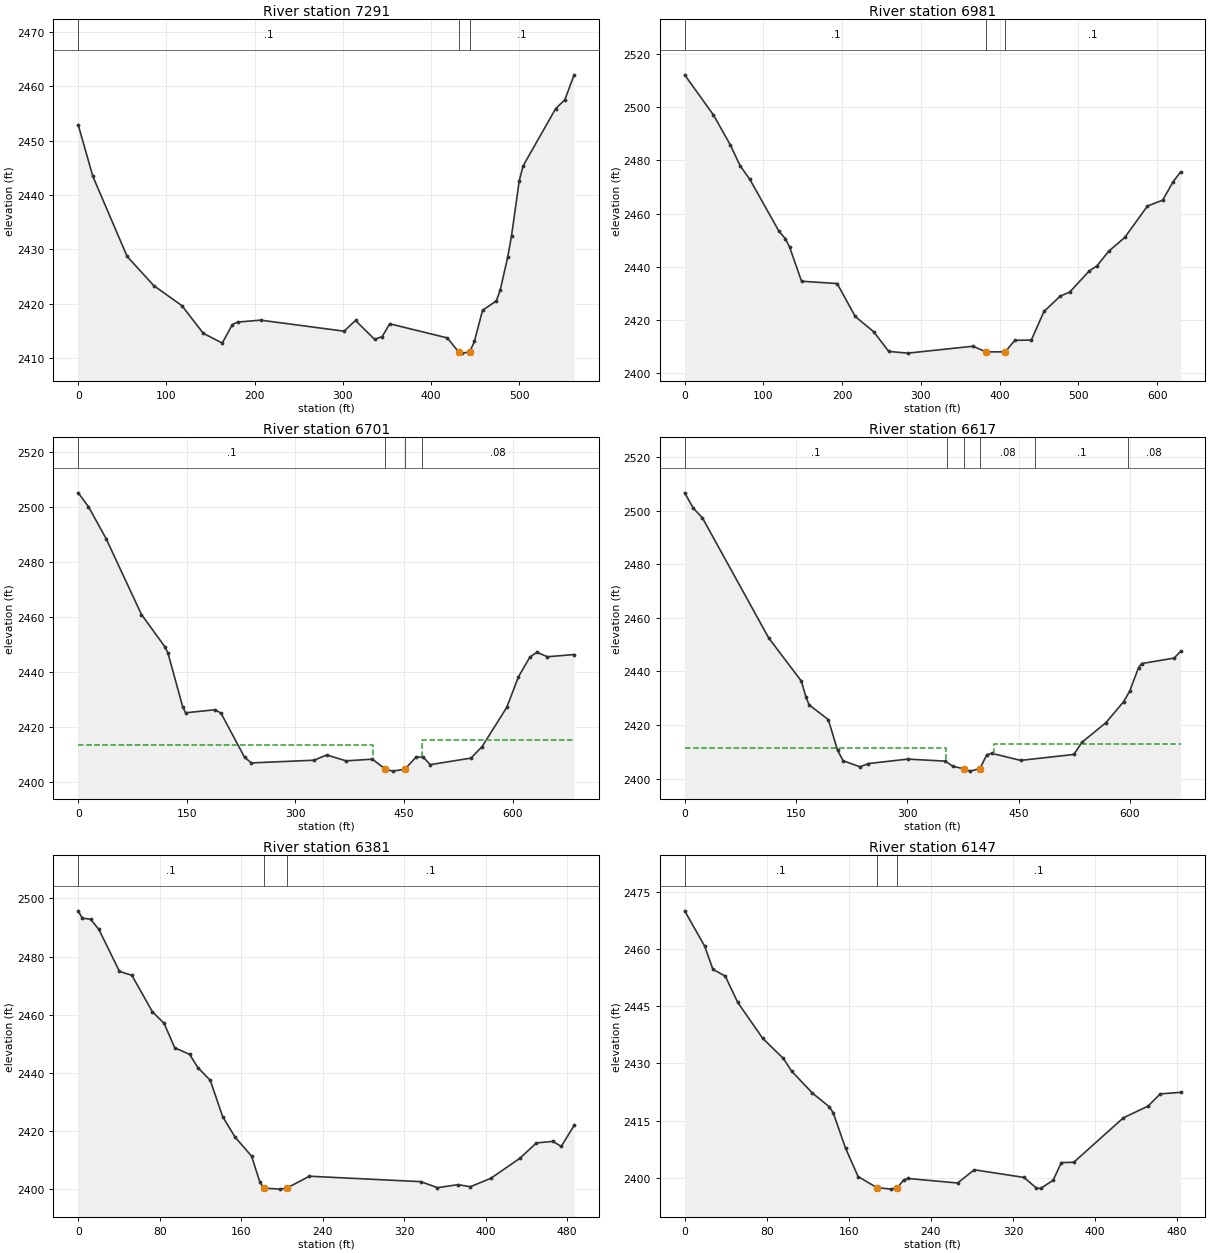
Type RM Length L Ch R = 1 ,7291    ,312.4,310.3,306.6
XS GIS Cut Line= 2
2242168.78642168 631867.582825422242689.93838617632078.663928356
#Sta/Elev= 30
       0 2452.91    16.6 2443.43    55.4 2428.71    85.7 2423.32   117.5 2419.65
   141.8 2414.55   163.3 2412.75   174.7 2416.14   180.6 2416.61   206.7 2416.97
   301.4 2414.94   314.4 2416.91     336 2413.44   344.6 2413.94   353.2  2416.3
   418.5  2413.7   431.2 2411.14   435.2  2410.9   443.9 2411.12   449.2 2413.06
   458.4 2418.77   474.1 2420.52   478.4 2422.47     487 2428.59   491.3  2432.5
     500 2442.58   504.3 2445.32   541.4 2455.91   551.7 2457.51   562.3 2462.11
#Mann= 3 ,-1,0
       0      .1       0   431.2    .045       0   443.9      .1       0
Bank Sta=431.2,443.9
XS Rating Curve= 0 ,0
Exp/Cntr(USF)=0,0
Exp/Cntr=0.3,0.1

Type RM Length L Ch R = 1 ,6981    ,270.9,279.2,289.1
BEGIN DESCRIPTION:
Structure XS 4
END DESCRIPTION:
XS GIS Cut Line= 2
2242031.55004695632206.1031777072242645.26714745 632347.39056775
#Sta/Elev= 30
       0 2512.02    36.5 2496.98    58.1 2485.67    70.4 2477.91    82.7 2472.84
   119.7 2453.37   127.9 2450.56   133.2 2447.46   148.4  2434.6   193.6 2433.75
   216.6 2421.38     240 2415.67   259.2 2408.27   283.4 2407.64     366 2410.22
   382.82408.112     407 2408.13   419.3 2412.45   440.2 2412.53   456.3 2423.28
   476.8    2429   489.1 2430.58   513.7 2438.45   523.6 2440.39   538.3  2445.8
   558.9 2451.03   587.6 2462.79     607 2465.02   620.3 2471.93   629.8 2475.61
#Mann= 3 ,-1,0
       0      .1       0   382.8    .045       0     407      .1       0
Bank Sta=382.8,407
XS Rating Curve= 0 ,0
Exp/Cntr(USF)=0,0
Exp/Cntr=0.3,0.1

Type RM Length L Ch R = 1 ,6701    ,86,84.6,82.4
BEGIN DESCRIPTION:
Structure XS 3
END DESCRIPTION:
XS GIS Cut Line= 6
2242030.22547767632321.1199436642242234.87143168632358.870168191
2242306.39817289  632509.87106632242373.95120626632607.226908501
2242431.56997001632652.9245487182242548.79435143632664.845672253
#Sta/Elev= 30
       0 2505.26    14.2 2500.19    38.6 2488.54    87.4 2460.95   119.9 2449.14
     124 2446.88   144.3  2427.4   148.4 2425.16   189.1 2426.28   197.2 2425.04
   229.8 2408.97   239.2 2406.91   325.7 2407.89   343.4 2409.81     370 2407.66
   406.4 2408.28   424.42404.619   434.4 2403.92  451.232404.622   466.8 2409.07
   476.6 2409.03   486.3 2406.27   542.5 2408.67   557.8  2412.8     592 2427.14
   608.1 2438.25   624.1  2445.5   633.7 2447.19   648.2 2445.57   685.1 2446.38
#Mann= 4 ,-1,0
       0      .1       0   424.4    .045       0  451.23      .1       0
  475.18     .08       0
#XS Ineff= 2 , 0
          406.77 2413.42   475.2         2415.42
Permanent Ineff=
       F       F
Bank Sta=424.4,451.23
XS Rating Curve= 0 ,0
Exp/Cntr(USF)=0,0
Exp/Cntr=0.3,0.1

Type RM Length L Ch R = 1 ,6617    ,241.4,235.7,225.1
BEGIN DESCRIPTION:
Structure XS 2
END DESCRIPTION:
XS GIS Cut Line= 6
2241996.44896099  632430.39690942242157.38412871632452.252302548
 2242262.6873866632587.358369276 2242342.1615435632688.687919323
2242409.71457686632720.4775820822242540.84693574 632726.43814385
#Sta/Elev= 30
       0 2506.65    11.8 2500.85    23.9 2497.32   113.2 2452.51   157.2  2436.4
   163.6  2430.3   167.9 2427.45   193.6 2422.01     206 2410.58   213.5 2406.66
   236.3 2404.39   247.7  2405.6   300.5 2407.27   351.3 2406.51   361.4 2404.59
   376.7 2403.62   384.5 2402.78  397.812403.702   407.2 2408.91   413.9 2409.41
   452.8 2406.79   524.5 2409.01   535.4 2413.55   567.6 2420.83   591.7 2428.72
   599.7  2432.6   611.7 2441.39   615.7 2442.91   659.7 2444.98   668.4 2447.47
#Mann= 6 ,-1,0
       0      .1       0  353.71     .08       0   376.7    .045       0
  397.81     .08       0  472.49      .1       0  597.15     .08       0
#XS Ineff= 2 , 0
          351.81 2411.25  416.71         2412.91
Permanent Ineff=
       F       F
Bank Sta=376.7,397.81
XS Rating Curve= 0 ,0
Exp/Cntr(USF)=0,0
Exp/Cntr=0.3,0.1

Type RM Length L Ch R = 1 ,6381    ,236.2,233.9,229.5
BEGIN DESCRIPTION:
Structure XS 1
END DESCRIPTION:
XS GIS Cut Line= 2
  2241956.249587 632764.313579962242436.64106265632842.923094157
#Sta/Elev= 30
       0 2495.73       4  2493.2    12.1 2492.85    20.2 2489.37    40.5 2474.88
    52.6 2473.56    72.9 2460.96    84.3 2457.03    94.7 2448.62   109.4 2446.32
   117.5 2441.74   129.6 2437.42   141.8  2424.9     154 2417.84   170.2  2411.3
   178.3 2402.38   182.3  2400.3   198.5 2399.96  204.672400.299   226.9  2404.4
   336.3 2402.53   352.6 2400.47   372.8 2401.49     385 2400.79   405.2 2403.72
   433.6  2410.6   449.8 2415.87     466 2416.39   474.1 2414.65   486.8 2421.88
#Mann= 3 ,-1,0
       0      .1       0   182.3    .045       0  204.67      .1       0
Bank Sta=182.3,204.67
XS Rating Curve= 0 ,0
Exp/Cntr(USF)=0,0
Exp/Cntr=0.3,0.1

Type RM Length L Ch R = 1 ,6147    ,220.2,222.4,222.3
XS GIS Cut Line= 3
2241964.98397747633055.4599288372242372.58886589632995.774927317
2242443.91972137632997.230659061
#Sta/Elev= 30
       0  2470.1    19.4 2460.86    27.5 2454.74    39.6 2452.93    51.7 2446.04
      76 2436.62    96.2 2431.31   104.3 2427.96   124.5 2422.21   140.7 2418.68
   144.7  2417.1   156.8 2407.72     169  2400.3  187.222397.386   201.3 2396.99
  207.382397.391   213.4  2399.4   217.5 2399.79     266  2398.6   282.2 2402.07
   330.7 2400.06   342.8 2397.26   346.9 2397.19     359  2399.3   367.1 2403.96
   379.2 2404.05   427.5 2415.72   451.5 2418.79   463.5 2422.01   483.3 2422.42
#Mann= 3 ,-1,0
       0      .1       0  187.22    .045       0  207.38      .1       0
Bank Sta=187.22,207.38
XS Rating Curve= 0 ,0
Exp/Cntr(USF)=0,0
Exp/Cntr=0.3,0.1