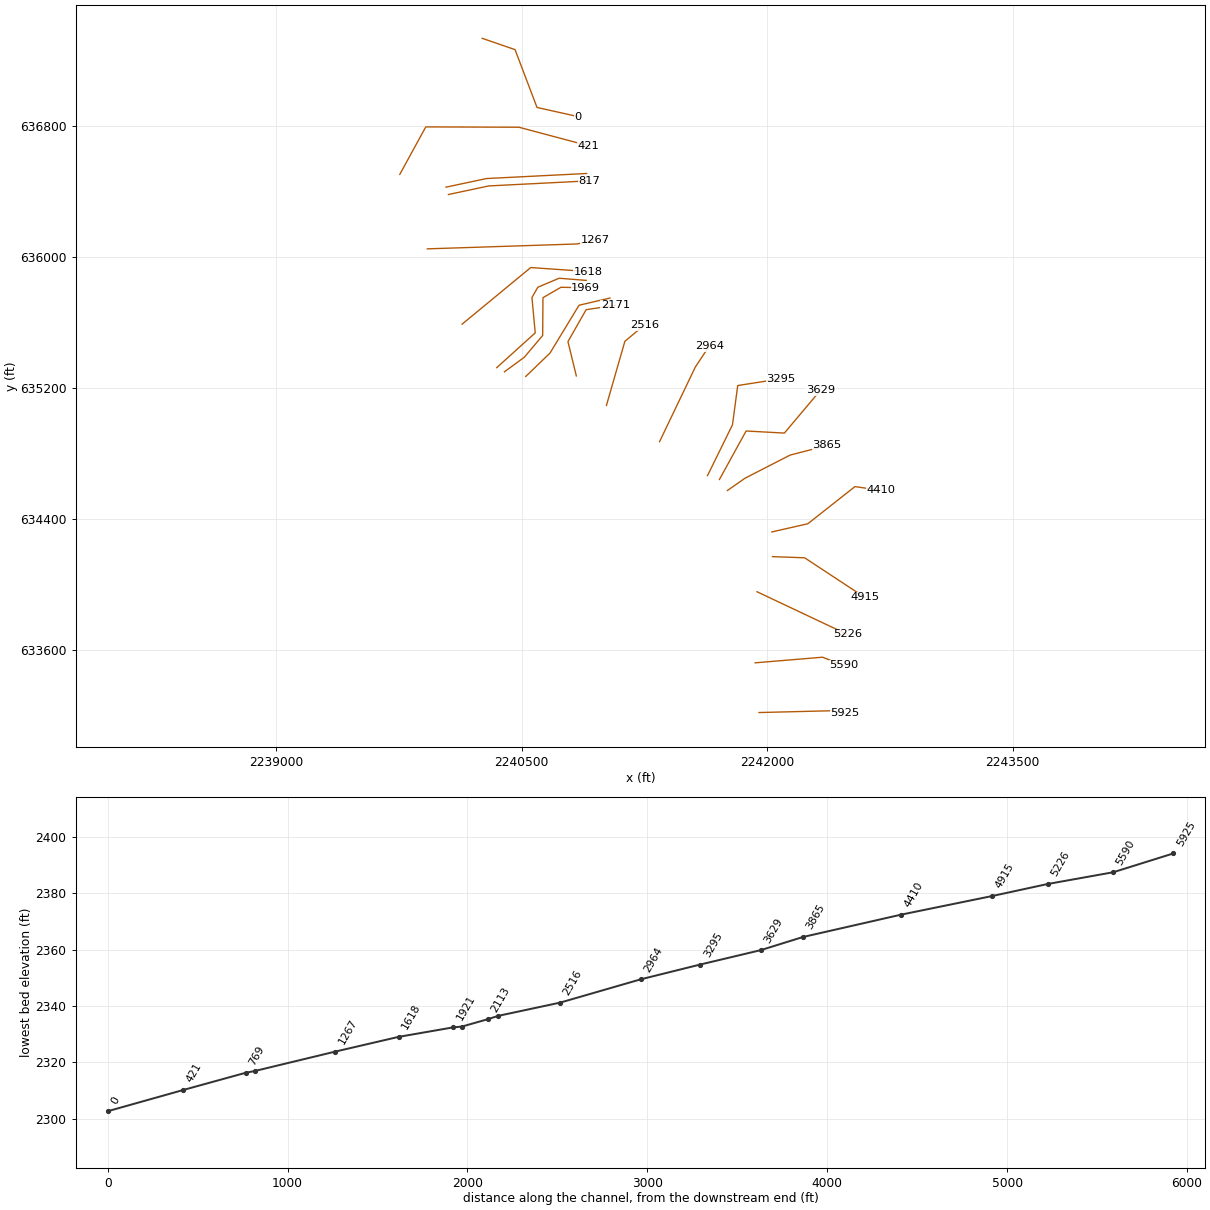
HEC-RAS study KITTLECK.prj: KITTLECK

--- KITTLECK.g01 (geometry) --- (continued)

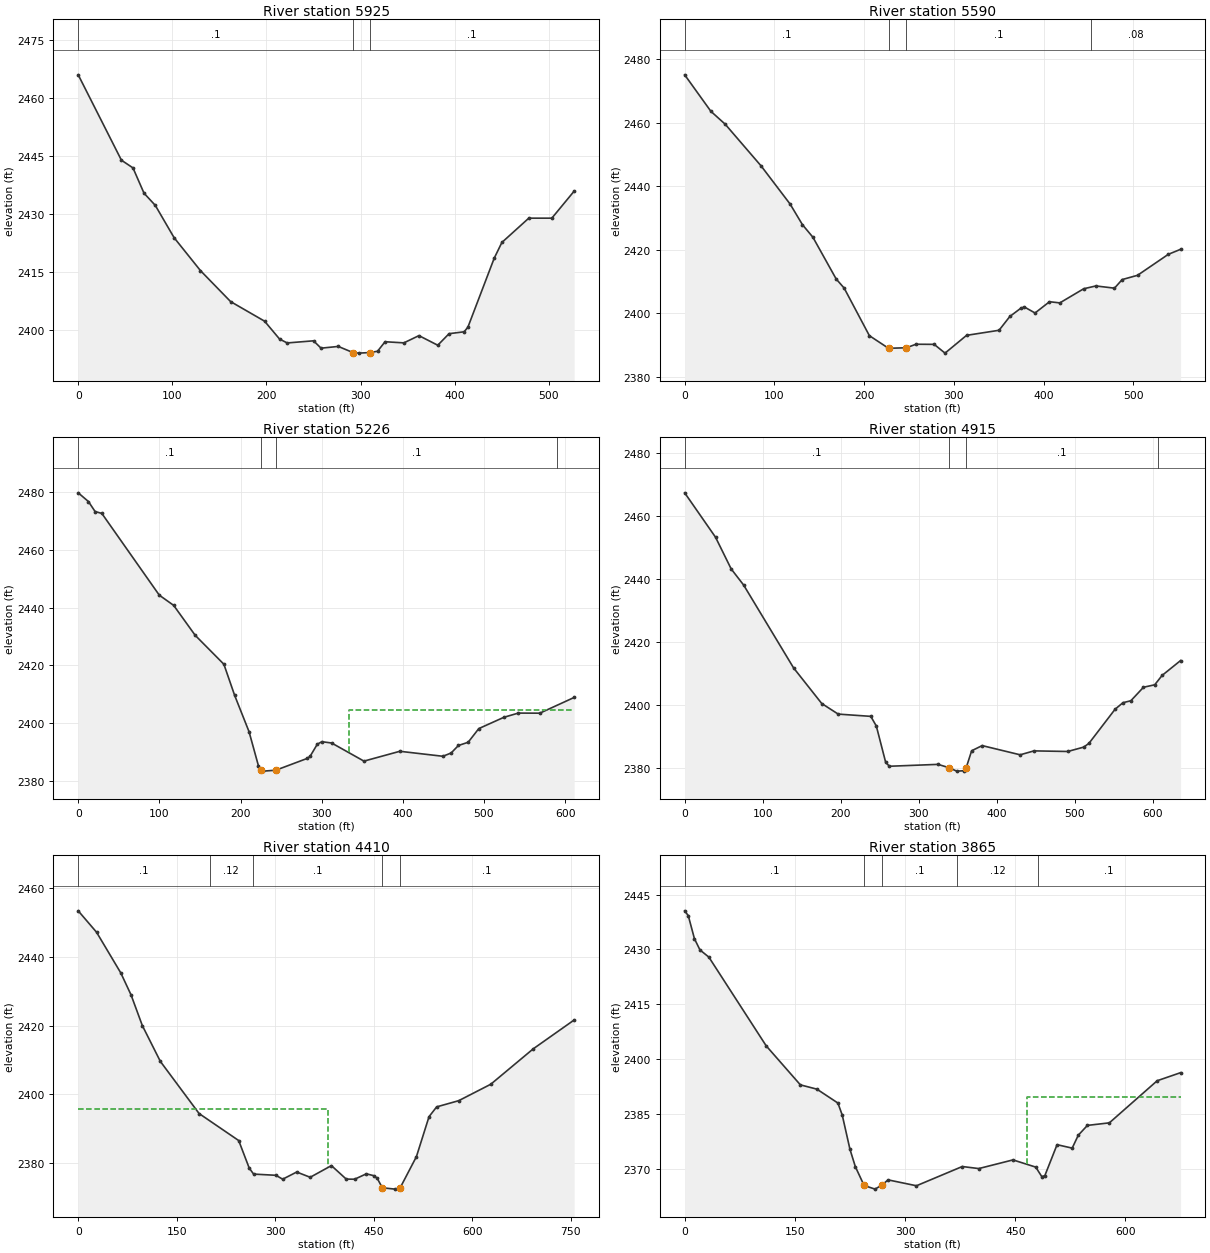
Type RM Length L Ch R = 1 ,5925    ,334.3,335.3,334.8
XS GIS Cut Line= 3
2241950.28494655633215.9906471062242399.11524764633227.087045639
2242475.34162087633210.913061283
#Sta/Elev= 30
       0 2465.98    45.9 2443.94    58.2 2441.94    69.9 2435.42    81.9 2432.27
   101.9 2423.92   129.9 2415.42   161.9 2407.43     198 2402.37   213.9 2397.76
     222 2396.75     250  2397.3     258  2395.4   276.3 2395.85     292 2394.26
     298 2394.12     310 2394.27     318  2394.6     326 2397.06     346 2396.77
     362 2398.64     382 2396.16     394 2399.14     410 2399.63     414 2400.81
     442 2418.65   450.1 2422.69   478.7 2428.97   503.2 2428.97   526.9 2435.95
#Mann= 3 ,-1,0
       0      .1       0     292    .045       0     310      .1       0
Bank Sta=292,310
XS Rating Curve= 0 ,0
Exp/Cntr(USF)=0,0
Exp/Cntr=0.3,0.1

Type RM Length L Ch R = 1 ,5590    ,366,363.1,356.6
XS GIS Cut Line= 3
2241927.11922324633520.0248142622242338.39798519633554.251985539
 2242468.9342879 633503.93129749
#Sta/Elev= 30
       0 2475.08    29.2 2463.59    45.2 2459.51    85.3 2446.34   117.5 2434.37
   131.2 2427.89   142.9 2423.92   168.8 2410.78   177.7 2407.91   205.8 2392.93
227.15892388.953247.1465 2389.12   257.7 2390.23     278 2390.19   290.1 2387.43
   314.1 2393.03   350.3 2394.63   362.3 2398.97   374.3 2401.52   378.4 2401.98
   390.4 2400.07   406.5 2403.62     418 2403.25   444.6  2407.7   458.2 2408.59
   478.9 2407.89   487.5  2410.6   504.6 2411.94   538.9 2418.55   552.6 2420.13
#Mann= 4 ,-1,0
       0      .1       0227.1589    .045       0247.1465      .1       0
   452.7     .08       0
Bank Sta=227.1589,247.1465
XS Rating Curve= 0 ,0
Exp/Cntr(USF)=0,0
Exp/Cntr=0.3,0.1

Type RM Length L Ch R = 1 ,5226    ,311.8,311.8,310.1
XS GIS Cut Line= 2
2241937.84823442633954.5497671082242490.39231026633693.477161695
#Sta/Elev= 30
       0  2479.8    12.6 2476.78    20.8 2473.31    29.1 2472.66    99.9 2444.31
   117.6 2440.77   144.1  2430.4   179.5 2420.35   192.8 2409.52   210.5 2396.96
   222.1  2385.1   225.52383.549   228.2 2383.28   243.52383.599   282.2 2387.69
   285.7  2388.4   294.6 2392.61   300.2 2393.49   312.3 2393.03   352.1 2386.75
   396.3 2390.16   449.4 2388.43   459.5 2389.57   468.5 2392.17   480.5 2393.29
   493.6 2398.03   524.6 2401.96   542.3 2403.41   568.8 2403.38   611.1 2408.83
#Mann= 4 ,-1,0
       0      .1       0   225.5    .045       0   243.5      .1       0
     590     .08       0
#XS Ineff= 2 , 0
                          333.07         2404.48
Permanent Ineff=
       F       F
Bank Sta=225.5,243.5
XS Rating Curve= 0 ,0
Exp/Cntr(USF)=0,0
Exp/Cntr=0.3,0.1

Type RM Length L Ch R = 1 ,4915    ,488,504.3,520.6
XS GIS Cut Line= 3
2242032.62116652634169.1299907362242229.31970485634161.977316615
2242595.89425354633920.574565034
#Sta/Elev= 30
       0 2467.49    39.6 2453.35    59.6 2443.29    75.6 2438.15   139.6 2411.81
   175.7 2400.48   196.8 2397.11   238.6 2396.39   245.7 2393.31   257.7 2381.75
   262.5 2380.52   324.8 2381.12  339.11 2380.04   348.7 2378.97   358.3 2379.09
   360.92380.042   367.9 2385.45   381.4 2387.09   430.1 2384.16   447.8 2385.41
   491.1 2385.22   511.6 2386.61   518.3 2387.81   551.8 2398.66   561.9 2400.74
     572 2401.35   588.2 2405.65   602.6 2406.43   612.1 2409.42   635.8 2414.15
#Mann= 4 ,-1,0
       0      .1       0  339.11    .045       0   360.9      .1       0
  606.83     .08       0
Bank Sta=339.11,360.9
XS Rating Curve= 0 ,0
Exp/Cntr(USF)=0,0
Exp/Cntr=0.3,0.1

Type RM Length L Ch R = 1 ,4410    ,541.9,545.5,538.8
XS GIS Cut Line= 4
2242028.97492833634320.1164389982242248.91965755634370.185157845
2242536.81479092634597.2825611842242697.74995864634574.036370291
#Sta/Elev= 30
       0 2453.47    27.9 2447.24    64.8 2435.38    80.4 2428.99    97.6 2420.04
     125 2409.61     184 2394.41   244.3 2386.54   260.3 2378.52     267 2376.77
     301 2376.42   311.2 2375.28   332.6 2377.37   353.1 2375.84   385.4 2379.24
     408 2375.31   420.8 2375.28   438.6 2376.85     450  2376.3     455 2375.59
   462.9 2372.78   482.3 2372.39  490.07 2372.78   514.8 2381.85     534  2393.5
   545.6 2396.35   579.2 2398.16     628 2402.95   692.6 2413.26   754.9 2421.67
#Mann= 5 ,-1,0
       0      .1       0     200     .12       0  265.57      .1       0
   462.9    .045       0  490.07      .1       0
#XS Ineff= 2 , 0
          380.65 2395.86
Permanent Ineff=
       F       F
Bank Sta=462.9,490.07
XS Rating Curve= 0 ,0
Exp/Cntr(USF)=0,0
Exp/Cntr=0.3,0.1

Type RM Length L Ch R = 1 ,3865    ,238.7,235.3,226
XS GIS Cut Line= 4
2241757.24321287634573.2560785682241864.53332468634648.359156838
2242139.91127834634789.6244707262242367.00868168634848.634032224
#Sta/Elev= 30
       0 2440.54     4.9 2439.22    13.3 2432.91    20.8 2429.85    32.9 2427.89
     111 2403.62   157.5 2392.96     180 2391.79   208.6 2387.99   214.5 2384.69
     225 2375.34   232.3 2370.61   244.2 2365.47   259.1 2364.46     268 2365.51
   276.9 2366.99   315.5 2365.38   377.9 2370.64   400.3 2370.08   446.9 2372.45
   477.9 2370.48   486.2 2367.85   490.3 2368.16   506.9 2376.61   527.5 2375.67
   535.8  2379.2   548.2 2381.88   578.1 2382.58   643.2 2394.09   675.1  2396.3
#Mann= 5 ,-1,0
       0      .1       0   244.2    .045       0     268      .1       0
  370.96     .12       0  480.46      .1       0
#XS Ineff= 2 , 0
                          465.99         2389.66
Permanent Ineff=
       F       F
Bank Sta=244.2,268
XS Rating Curve= 0 ,0
Exp/Cntr(USF)=0,0
Exp/Cntr=0.3,0.1

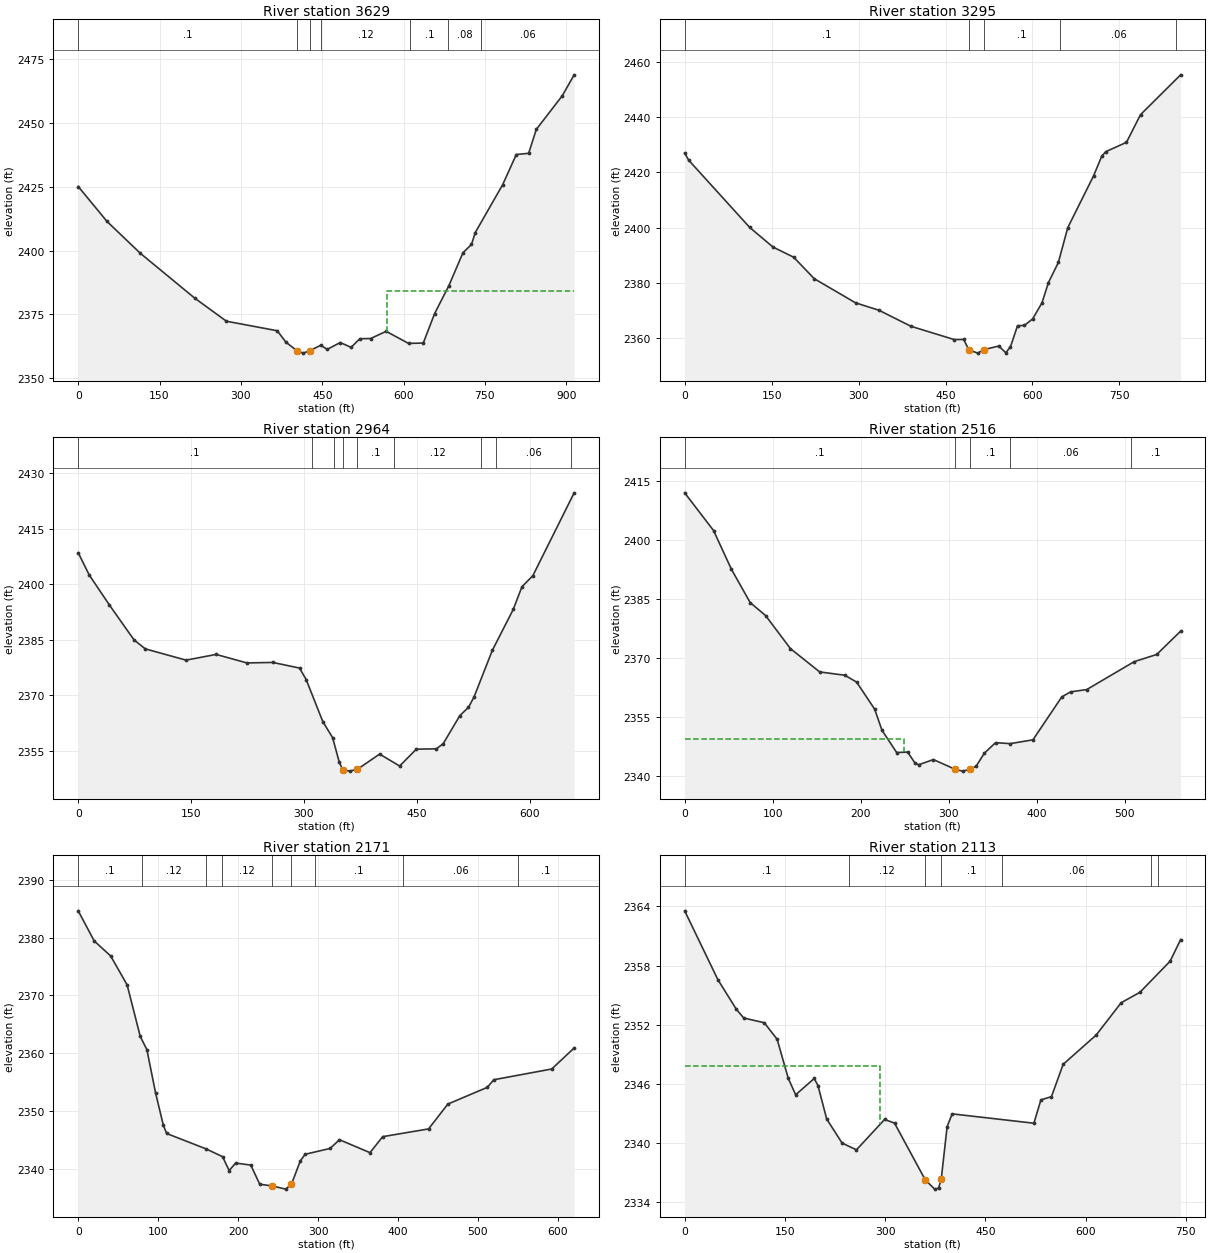
Type RM Length L Ch R = 1 ,3629    ,310.7,334.9,348.2
XS GIS Cut Line= 4
  2241708.458735634640.7266184472241871.49701581634937.159856301
2242105.46753569634924.4555746782242325.67508381635185.952038071
#Sta/Elev= 30
       0 2425.15    53.1 2411.45   114.6 2398.94   215.2  2381.3   273.3 2372.31
     367 2368.57   383.1 2364.07   403.5 2360.71   414.9 2359.79   427.12360.752
   447.1 2362.87   459.2 2361.27   483.2 2363.95   503.2 2362.06   519.3 2365.44
   539.3 2365.52   567.8 2368.35   609.1  2363.6   636.3 2363.75   657.2 2375.31
   683.4 2386.22   709.5 2399.18   725.2 2402.42   732.1 2407.07   782.7 2425.87
   807.8 2437.69   830.6 2438.18   844.7 2447.55   892.6 2460.76   914.5 2468.96
#Mann= 7 ,-1,0
       0      .1       0   403.5    .045       0   427.1      .1       0
  448.31     .12       0  612.63      .1       0  682.63     .08       0
  742.63     .06       0
#XS Ineff= 2 , 0
                          570.01         2384.29
Permanent Ineff=
       F       F
Bank Sta=403.5,427.1
XS Rating Curve= 0 ,0
Exp/Cntr(USF)=0,0
Exp/Cntr=0.3,0.1

Type RM Length L Ch R = 1 ,3295    ,333.2,330.4,328
XS GIS Cut Line= 4
2241635.64775281 634664.452673612241788.10695849634974.813585403
2241820.33761156635215.111302062 2242084.4780539635256.336457117
#Sta/Elev= 30
       0 2426.97     6.9 2424.39   112.2  2400.1   152.3 2393.03     188 2389.35
   223.6 2381.58   294.9 2372.86   335.1  2370.2   390.4  2364.4     465 2359.61
   481.4 2359.64  490.12 2355.91   505.6 2354.71   515.82355.959   541.9 2357.27
     554 2354.85   562.1 2357.01   574.2 2364.59   586.2 2364.74   600.4 2367.09
   616.4 2372.86   627.6  2380.2   644.7 2387.47   660.9 2400.02   705.5 2418.75
   719.5 2425.82   726.5 2427.46   762.2 2430.84   786.4 2440.82   855.6 2455.21
#Mann= 5 ,-1,0
       0      .1       0  490.12    .045       0   515.8      .1       0
  648.24     .06       0  848.24      .1       0
Bank Sta=490.12,515.8
XS Rating Curve= 0 ,0
Exp/Cntr(USF)=0,0
Exp/Cntr=0.3,0.1

Type RM Length L Ch R = 1 ,2964    ,446.1,448.6,449.3
XS GIS Cut Line= 3
2241342.56152895634871.9365434112241560.63470866635327.398430788
2241645.74716953635455.822095346
#Sta/Elev= 30
       0 2408.51    14.7 2402.47    41.3 2394.43    74.1 2384.96    89.1 2382.52
   143.3 2379.47   183.2 2381.02   224.1 2378.72   258.6 2378.85   294.1 2377.33
   302.9 2374.22   325.1 2362.82     338 2358.54     347 2351.81  351.322349.896
   360.6 2349.47     371 2349.96   400.5 2354.08   427.1 2350.85   449.3 2355.41
   475.9  2355.5     485 2356.89   507.1 2364.48   518.6 2366.72   525.9 2369.48
   550.3 2382.13   578.1  2393.2   589.6  2399.3   604.1  2402.3     659  2424.7
#Mann= 9 ,-1,0
       0      .1       0     310     .12       0     340      .1       0
  351.32    .045       0     371      .1       0     420     .12       0
  534.98      .1       0  554.98     .06       0  654.98      .1       0
Bank Sta=351.32,371
XS Rating Curve= 0 ,0
Exp/Cntr=0.3,0.1

Type RM Length L Ch R = 1 ,2516    ,346.8,344.9,341.7
XS GIS Cut Line= 3
2241017.85783164635093.6874128112241130.51244905635485.296320931
2241250.31974057635585.433758624
#Sta/Elev= 30
       0 2411.94    32.8 2402.36    53.2 2392.47    74.4 2384.06      92 2380.73
   120.2 2372.34   153.4 2366.42     182 2365.57   195.4 2363.83   215.9 2356.95
   224.2  2351.6   240.9 2345.93   253.4 2346.04   261.7 2343.26   265.9 2342.82
   282.7 2344.14   307.5 2341.65   315.8  2341.2   324.7 2341.67   331.2 2342.45
   340.6 2345.77   353.3 2348.43     370 2348.19   395.8 2349.16   428.5 2360.05
   438.5 2361.35   456.9 2361.93   510.8 2369.02   536.4 2370.85   563.6 2376.78
#Mann= 5 ,-1,0
       0      .1       0   307.5    .045       0   324.7      .1       0
     370     .06       0  507.49      .1       0
#XS Ineff= 2 , 0
          249.35 2349.33
Permanent Ineff=
       F       F
Bank Sta=307.5,324.7
XS Rating Curve= 0 ,0
Exp/Cntr(USF)=0,0
Exp/Cntr=0.3,0.1

Type RM Length L Ch R = 1 ,2171    ,57.8,57.5,57
XS GIS Cut Line= 4
2240833.78096206635273.7640060222240782.55582659635483.497107826
2240893.70470543635678.7325297812241071.54291157635705.794865498
#Sta/Elev= 30
       0 2384.65      20 2379.44    40.6 2376.84    61.2 2371.83    77.6 2362.91
    85.9 2360.63    96.8 2353.12   106.5 2347.54   110.6 2346.12     160 2343.45
   180.6  2342.1   188.8 2339.71     197    2341   215.9 2340.65   227.1 2337.33
   242.62337.051   259.4 2336.49   266.82337.339   277.7 2341.33   283.8 2342.52
   315.1 2343.53   326.8 2345.04     365  2342.8   380.9 2345.57   438.3 2346.91
   462.4 2351.21   511.6 2354.09   519.9 2355.42   592.4 2357.28   620.4 2360.92
#Mann= 9 ,-1,0
       0      .1       0      80     .12       0     160      .1       0
     180     .12       0   242.6    .045       0   266.8     .12       0
   295.9      .1       0   405.9     .06       0  550.56      .1       0
Bank Sta=242.6,266.8
XS Rating Curve= 0 ,0
Exp/Cntr(USF)=0,0
Exp/Cntr=0.3,0.1

Type RM Length L Ch R = 1 ,2113    ,139.1,143.7,152.5
BEGIN DESCRIPTION:
Structure XS 4
END DESCRIPTION:
XS GIS Cut Line= 4
2240524.50193396635270.5155440652240672.41960346635412.954781361
2240850.46865008635706.0509042592241039.47456111635749.878361888
#Sta/Elev= 30
       0 2363.56    49.7 2356.57    77.3 2353.57    88.4 2352.68   119.2  2352.2
   138.4 2350.52     155 2346.56   166.1 2344.89   193.9 2346.54   199.5 2345.82
   212.6 2342.42   235.7 2339.98   257.1  2339.3   299.2 2342.38   314.1 2342.01
   360.1 2336.25   374.2 2335.31     380 2335.41  384.052336.347   392.8 2341.65
   400.4 2342.95   522.7    2342   533.2 2344.37     549  2344.7   566.5 2347.98
   615.9 2350.95   653.3 2354.23   681.4 2355.29   726.6 2358.45   742.3 2360.64
#Mann= 7 ,-1,0
       0      .1       0  245.35     .12       0   360.1    .045       0
  384.05      .1       0  475.35     .06       0  698.29      .1       0
  708.29     .05       0
#XS Ineff= 2 , 0
          292.85 2347.78
Permanent Ineff=
       F       F
Bank Sta=360.1,384.05
XS Rating Curve= 0 ,0
Exp/Cntr(USF)=0,0
Exp/Cntr=0.3,0.1

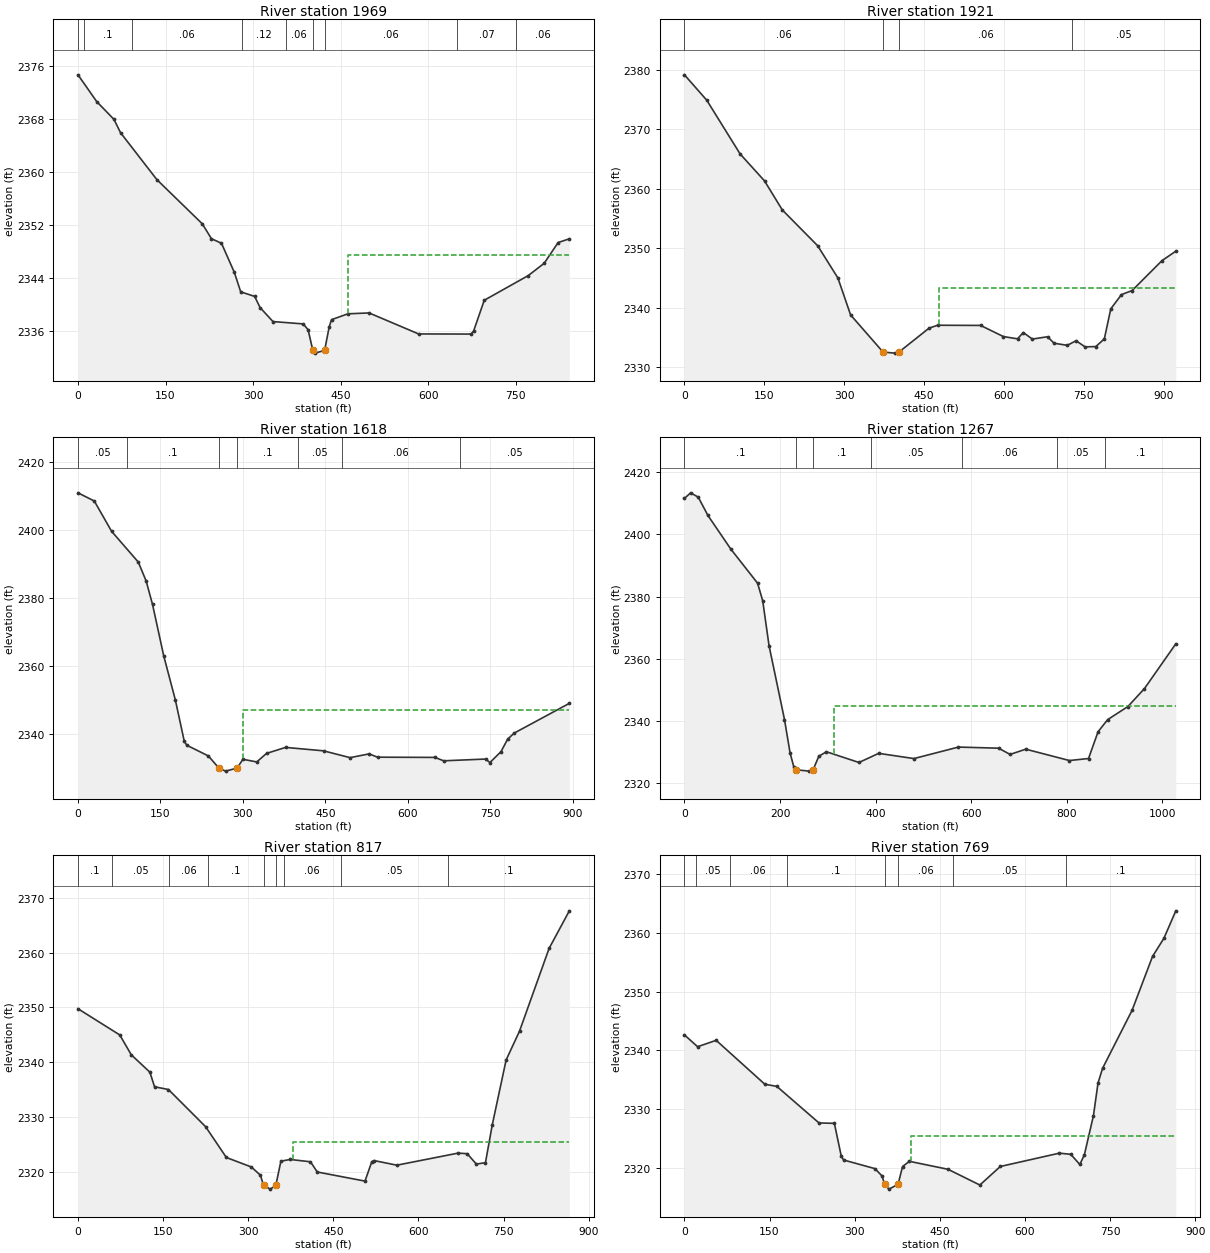
Type RM Length L Ch R = 1 ,1969    ,49.2,48.9,48.8
BEGIN DESCRIPTION:
Structure XS 3
END DESCRIPTION:
XS GIS Cut Line= 6
 2240394.5487097635299.0368398462240516.11533988635388.244007312
2240628.06158924635521.1801784362240629.81074939635752.069317759
2240740.00783861635815.9136631022240891.31019128635812.415342809
#Sta/Elev= 30
       0  2374.6    32.1 2370.57    61.6  2367.9    72.9 2365.89   135.2 2358.82
   213.1 2352.16   228.6 2349.93   245.9 2349.24   267.9 2344.86   278.8 2341.93
   302.7 2341.24     312 2339.56   334.1 2337.45   385.9  2337.1   394.3 2336.22
   402.4 2333.11   406.4  2332.7   422.6 2333.12   430.5 2336.68   434.5 2337.74
   462.6 2338.62   498.8 2338.75   583.6 2335.59   673.7 2335.57   677.9 2336.03
   696.1 2340.66   771.6 2344.38   798.7 2346.22   822.7 2349.35   841.9 2349.91
#Mann= 9 ,-1,0
       0     .06       0      10      .1       0   92.27     .06       0
  281.53     .12       0  355.89     .06       0   402.4    .045       0
   422.6     .06       0  649.33     .07       0  750.51     .06       0
#XS Ineff= 2 , 0
                          463.44         2347.47
Permanent Ineff=
       F       F
Bank Sta=402.4,422.6
XS Rating Curve= 0 ,0
Exp/Cntr(USF)=0,0
Exp/Cntr=0.3,0.1

Type RM Length L Ch R = 1 ,1921    ,317.2,303,287.4
BEGIN DESCRIPTION:
Structure XS 2
END DESCRIPTION:
XS GIS Cut Line= 6
2240347.32138575635324.3996619692240582.58342544635536.922619754
2240562.46808376635752.9438978322240598.32586676635815.913663102
2240728.63829766635871.012207713 2240893.9339315635857.893506615
#Sta/Elev= 30
       0 2379.13    41.8 2374.88   104.6 2365.84   150.4 2361.32   183.7 2356.45
   250.2 2350.43   288.1 2345.03     312 2338.82   372.9 2332.59   394.8 2332.41
   402.9  2332.6   459.1 2336.59   475.2 2337.09   556.1 2337.06   598.9 2335.19
   625.4 2334.81   636.2 2335.87   653.2 2334.77   681.7 2335.16   694.1 2334.07
   718.9 2333.72   735.4 2334.49   752.2 2333.46   772.4 2333.51   788.4  2334.8
   800.5 2339.84   820.5 2342.23   840.6 2342.92   896.8 2347.95   922.6 2349.52
#Mann= 4 ,-1,0
       0     .06       0   372.9    .045       0   402.9     .06       0
  727.03     .05       0
#XS Ineff= 2 , 0
                          477.08         2343.28
Permanent Ineff=
       F       F
Bank Sta=372.9,402.9
XS Rating Curve= 0 ,0
Exp/Cntr(USF)=0,0
Exp/Cntr=0.3,0.1

Type RM Length L Ch R = 1 ,1618    ,359.9,351,337.3
BEGIN DESCRIPTION:
Structure XS 1
END DESCRIPTION:
XS GIS Cut Line= 3
2240135.57369654635590.2877927122240555.29318086635936.420094708
2240904.15093404635911.891033937
#Sta/Elev= 30
       0 2411.06    29.7 2408.64    61.1 2399.73   109.7 2390.65     124 2385.07
   135.6 2378.17   155.9 2363.06   177.1 2350.03   193.2 2337.95   197.8 2336.69
   237.2 2333.52  256.482329.924   268.6 2329.05   289.5 2329.95     300 2332.54
   325.2 2331.76     343 2334.27   377.6 2336.04   446.7 2335.03   494.9 2333.02
   529.6 2334.13   544.9 2333.16   649.3 2333.09   665.2 2332.09   741.4 2332.61
   749.4 2331.58   769.5  2334.8   781.5 2338.45   793.5 2340.26   893.8 2349.02
#Mann= 7 ,-1,0
       0     .05       0      90      .1       0  256.48    .045       0
   289.5      .1       0     400     .05       0     480     .06       0
  694.03     .05       0
#XS Ineff= 2 , 0
                          300.36         2347.07
Permanent Ineff=
       F       F
Bank Sta=256.48,289.5
XS Rating Curve= 0 ,0
Exp/Cntr(USF)=0,0
Exp/Cntr=0.3,0.1

Type RM Length L Ch R = 1 ,1267    ,451.6,449.6,443.1
BEGIN DESCRIPTION:
Structure XS 4
END DESCRIPTION:
XS GIS Cut Line= 3
2239923.25003639636050.5999819682240839.00163852636080.579945133
2240948.01968639636105.109005905
#Sta/Elev= 30
       0 2411.59    12.9 2413.39    28.9 2411.99      49 2406.13      97 2395.29
     153 2384.32   163.8 2378.61     177 2364.19   209.3 2340.45     221 2329.68
     229 2325.09   234.1 2324.26   261.1 2323.84   269.1 2324.24   281.1 2328.62
   297.1 2330.07   365.1 2326.62   406.4 2329.56   480.1 2327.88   573.2 2331.58
   657.3 2331.22   681.3 2329.22   714.1  2330.9   805.4 2327.25   845.4  2327.9
   865.4 2336.52   885.4 2340.41   927.8 2344.63   962.5 2350.42    1028 2364.81
#Mann= 7 ,-1,0
       0      .1       0   234.1    .045       0   269.1      .1       0
     390     .05       0     580     .06       0     780     .05       0
     880      .1       0
#XS Ineff= 2 , 0
                          311.91         2344.66
Permanent Ineff=
       F       F
Bank Sta=234.1,269.1
XS Rating Curve= 0 ,0
Exp/Cntr(USF)=0,0
Exp/Cntr=0.3,0.1

Type RM Length L Ch R = 1 ,817     ,47.6,47.9,48.2
BEGIN DESCRIPTION:
Structure XS 3
END DESCRIPTION:
XS GIS Cut Line= 3
2240052.22996778636382.8734216692240299.42006717636435.412636206
2240911.78346627636466.369366415
#Sta/Elev= 30
       0 2349.77    73.6    2345      94 2341.37   126.7 2338.22   134.9 2335.56
   159.4 2335.06   224.9 2328.29   261.5 2322.68   305.5 2320.95   321.6 2319.45
  326.942317.596     339 2316.92   348.7 2317.63   357.6 2322.01     374 2322.32
   409.7  2321.9   421.7 2320.04   505.8 2318.38   517.8 2321.92   521.8 2322.12
   561.9 2321.28     670 2323.48     686 2323.37     702 2321.48   718.1 2321.74
   730.1 2328.64   754.5 2340.44   778.1 2345.69   830.2 2360.75   865.9  2367.6
#Mann= 9 ,-1,0
       0      .1       0      60     .05       0     160     .06       0
     230      .1       0  326.94    .045       0   348.7      .1       0
  362.71     .06       0  462.71     .05       0  652.71      .1       0
#XS Ineff= 2 , 0
                          379.18         2325.55
Permanent Ineff=
       F       F
Bank Sta=326.94,348.7
XS Rating Curve= 0 ,0
Exp/Cntr(USF)=0,0
Exp/Cntr=0.3,0.1

Type RM Length L Ch R = 1 ,769     ,344.6,348,347.3
BEGIN DESCRIPTION:
Structure XS 2
END DESCRIPTION:
XS GIS Cut Line= 3
2240037.48182533636427.8844934572240284.67192472636480.423707994
2240897.03532382636511.380438203
#Sta/Elev= 30
       0 2342.62    23.2 2340.61    55.9  2341.7   141.6 2334.22   162.8 2333.85
   237.1 2327.62   264.2 2327.55   276.2 2322.03   280.3 2321.31   335.8 2319.83
   348.3 2318.57  352.712317.162   360.4 2316.34   376.4 2317.15   384.4 2320.19
   396.4 2321.08   464.5 2319.72   520.6 2317.04   556.6  2320.2   660.7 2322.47
   680.8 2322.27   696.8 2320.54   704.8  2322.2   720.8 2328.88   728.8 2334.41
   736.8 2336.92   788.9 2346.83   824.9    2356     845  2359.1   865.9 2363.77
#Mann= 8 ,-1,0
       0      .1       0      20     .05       0      80     .06       0
     180      .1       0  352.71    .045       0   376.4     .06       0
  472.71     .05       0  672.71      .1       0
#XS Ineff= 2 , 0
                          399.01          2325.4
Permanent Ineff=
       F       F
Bank Sta=352.71,376.4
XS Rating Curve= 0 ,0
Exp/Cntr(USF)=0,0
Exp/Cntr=0.3,0.1

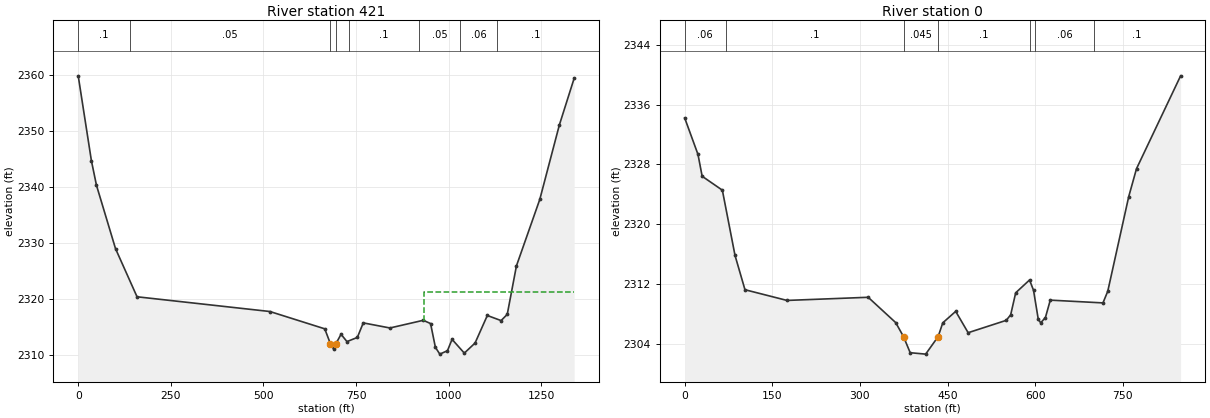
Type RM Length L Ch R = 1 ,421     ,435.7,421,394.1
BEGIN DESCRIPTION:
Structure XS 1
END DESCRIPTION:
XS GIS Cut Line= 4
2239754.78220934636505.9020059992239913.65674325636796.258912795
2240482.95526065636794.135871533 2240906.6580643636681.296978583
#Sta/Elev= 30
       0 2359.92    35.7 2344.72    49.3 2340.37   100.7 2329.06   158.8 2320.46
   517.5 2317.83   665.5 2314.74  681.042312.039   689.5 2311.13  694.992312.005
   709.5 2313.76   725.5 2312.46   753.5  2313.2   769.5  2315.8   841.5 2314.89
   931.5 2316.26   951.2 2315.68   964.2 2311.44   976.1 2310.22   996.8 2310.83
  1009.2 2312.86  1042.3  2310.4  1071.3  2312.2  1104.4 2317.12  1141.6 2316.21
  1158.2 2317.32    1183 2325.98    1246 2337.84  1298.9 2351.15  1338.8 2359.48
#Mann= 8 ,-1,0
       0      .1       0     140     .05       0  681.04    .045       0
  694.99     .05       0  730.98      .1       0  920.28     .05       0
 1030.28     .06       0 1130.28      .1       0
#XS Ineff= 2 , 0
                          933.33         2321.31
Permanent Ineff=
       F       F
Bank Sta=681.04,694.99
XS Rating Curve= 0 ,0
Exp/Cntr(USF)=0,0
Exp/Cntr=0.3,0.1

Type RM Length L Ch R = 1 ,0       ,,,
XS GIS Cut Line= 4
2240258.64113314637337.6025822582240459.20992929 637268.52283901
2240593.52684935636914.9760034592240845.95678648 636858.80540227
#Sta/Elev= 30
       0 2334.21    22.8 2329.33    29.9 2326.42    64.5 2324.56    86.2 2315.84
   103.2 2311.27   175.1 2309.84   314.1 2310.26   361.2 2306.88  374.562305.011
     386 2302.86   412.5 2302.67  433.862305.011   441.8 2306.85   463.9 2308.38
   485.2 2305.53   550.4 2307.18     558 2307.92   566.6 2310.86   590.3 2312.57
   597.1  2311.2   605.3  2307.3   609.4 2306.85   617.5 2307.56   625.8 2309.88
     716 2309.51   724.2 2311.07   760.1 2323.71   773.4 2327.43   848.9 2339.83
#Mann= 7 ,-1,0
       0     .06       0      70      .1       0  374.56    .045       0
  433.86      .1       0  590.33     .05       0  600.33     .06       0
  700.33      .1       0
Bank Sta=374.56,433.86
XS Rating Curve= 0 ,0
Exp/Cntr=0.3,0.1
LCMann Table=0

Chan Stop Cuts=-1
Use User Specified Reach Order=0
Composite Channel Slope=5